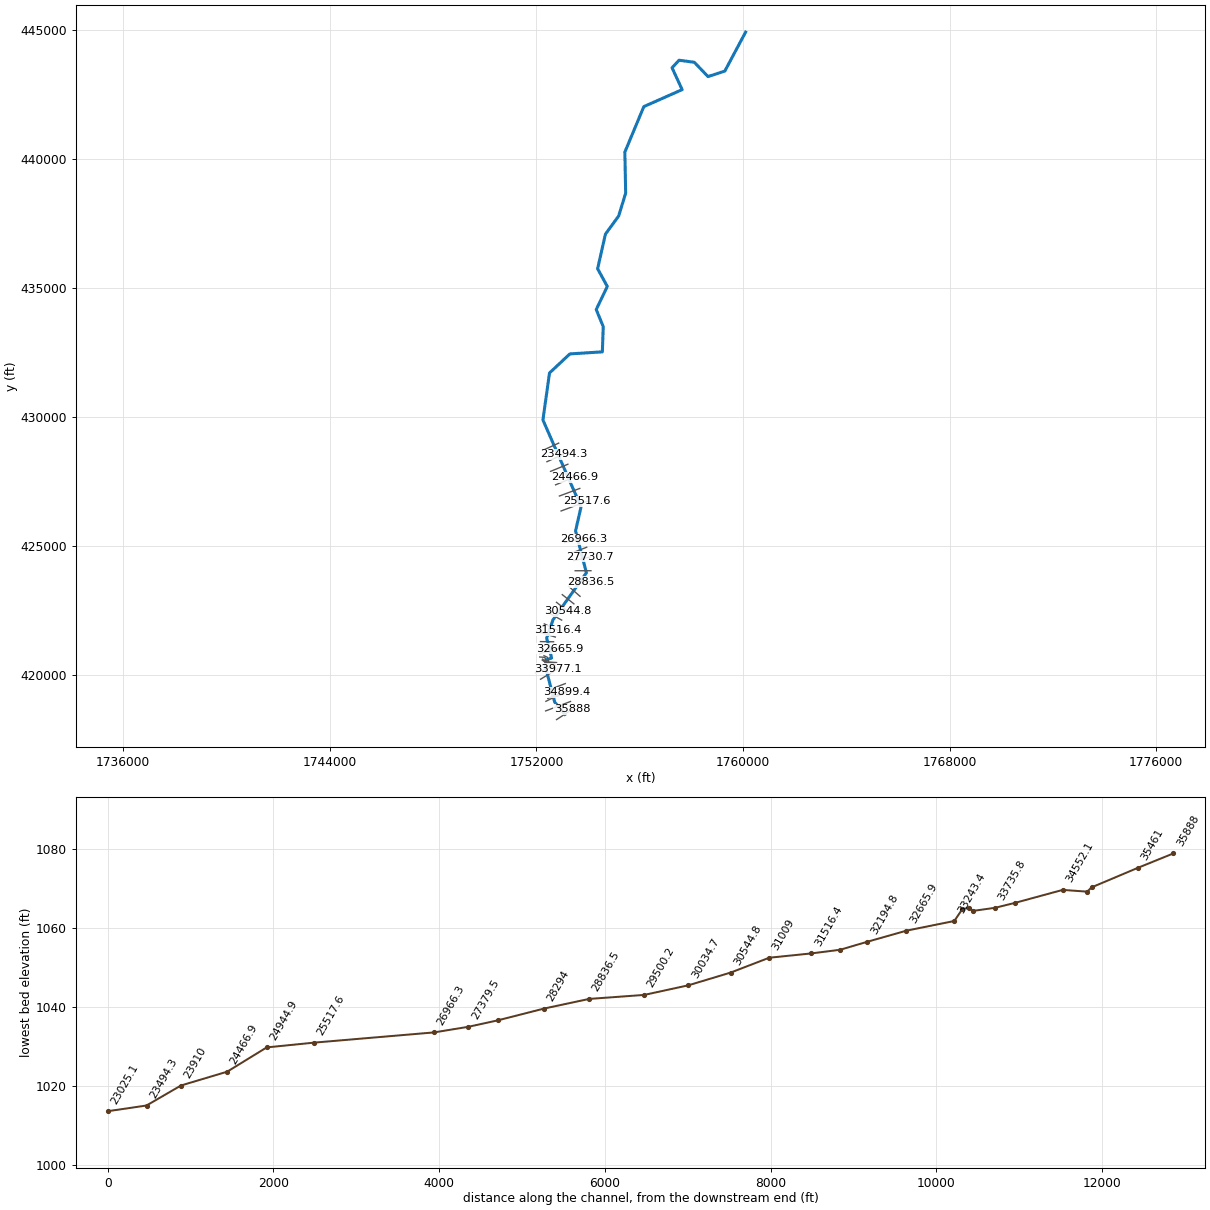
--- MiraclerRn.prj (project) ---

Proj Title=MiraclerRn
Current Plan=p01
Default Exp/Contr=0,0
English Units
Geom File=g01
Flow File=f01
Plan File=p01
BEGIN DESCRIPTION:
END DESCRIPTION:
DSS Export Rating Curves= 0
DSS Export Rating Curve Sorted= 0
DSS Export Volume Flow Curves= 0
DXF OffsetX= 0
DXF OffsetY= 0
DXF ScaleX= 0
DXF ScaleY= 0

--- MiraclerRn.p01 (plan) ---

Plan Title=Floodplain
Program Version=4.00
Geom File=g01
Flow File=f01
K Sum by GR=0
Std Step Tol=0.01
Critical Tol=0.01
Num of Std Step Trials=20
Max Error Tol=0.3
Flow Tol Ratio=0.001
Split Flow NTrial=30
Split Flow Tol=0.02
Split Flow Ratio=0.02
Log Output Level=0
Friction Slope Method=1
Unsteady Friction Slope Method=2
Unsteady Bridges Friction Slope Method=1
Global Log Level=0
CheckData=False
Run HTab=0
Run UNet=0
Run PostProcess=0
UNET Theta=0
UNET Theta Warmup=0
UNET ZTol=0
UNET ZSATol=0
UNET MxIter=0
UNET MaxInSteps=0
UNET DtIC=0
UNET DtMin=0
UNET MaxCRTS=0
UNET WFStab=0
UNET SFStab=0
UNET WFX=0
UNET SFX=0
UNET DSS MLevel=0
UNET DZMax Abort=0
UNET Convert EG Bridges=0
UNET Use Existing IB Tables=0
UNET Froude Limit=0
UNET Froude Power=0
Write IC File=0
Echo Input=False
Echo Output=False
Write Detailed=0

--- MiraclerRn.f01 (steady flow) ---

Flow Title=NFF Regression Equation
Program Version=4.10
Number of Profiles= 1
Profile Names=P100yr
River Rch & RM=MiraclerRn,Main            ,35888
     882
River Rch & RM=MiraclerRn,Main            ,32665.9
     923
River Rch & RM=MiraclerRn,Main            ,31009
     969
River Rch & RM=MiraclerRn,Main            ,30034.7
     993
River Rch & RM=MiraclerRn,Main            ,29500.2
    1006
River Rch & RM=MiraclerRn,Main            ,28836.5
    1012
River Rch & RM=MiraclerRn,Main            ,28294
    1175
River Rch & RM=MiraclerRn,Main            ,26966.3
    1214
River Rch & RM=MiraclerRn,Main            ,25517.6
    1377
River Rch & RM=MiraclerRn,Main            ,24944.9
    1478
River Rch & RM=MiraclerRn,Main            ,23494.3
    1546
River Rch & RM=MiraclerRn,Main            ,21039.4
    1609
River Rch & RM=MiraclerRn,Main            ,20597.3
    1991
River Rch & RM=MiraclerRn,Main            ,19350.2
    2083
River Rch & RM=MiraclerRn,Main            ,18182.2
    2097
River Rch & RM=MiraclerRn,Main            ,15530.5
    2219
River Rch & RM=MiraclerRn,Main            ,14351.7
    2328
River Rch & RM=MiraclerRn,Main            ,11981.2
    2455
River Rch & RM=MiraclerRn,Main            ,10230.5
    2499
River Rch & RM=MiraclerRn,Main            ,9892.1
    4279
River Rch & RM=MiraclerRn,Main            ,8187.6
    4291
River Rch & RM=MiraclerRn,Main            ,5149.1
    4578
River Rch & RM=MiraclerRn,Main            ,434.5
    4633
River Rch & RM=MiraclerRn,Main            ,59.3
    4638
Boundary for River Rch & Prof#=MiraclerRn,Main            , 1
Up Type= 0
Dn Type= 3
Dn Slope=0.002708
DSS Import GetInterval= 0
DSS Import GetPeak= 0
DSS Import FillOption= 0

--- MiraclerRn.g01 (geometry) ---

Geom Title=USGS 10m DEM
Program Version=4.10

River Reach=MiraclerRn      ,Main
Reach XY= 30
      1753105.21      418487.901     1752706.725      418963.954
     1752363.245      420277.832     1752361.113      420597.442
     1752588.328      420670.318     1752397.356      421444.624
     1752640.411      422146.013      1753935.55      423974.138
     1753515.564      425592.436      1753728.43      426524.675
     1752251.523      429887.332     1752506.731      431708.513
     1753294.925       432446.36     1754553.124      432525.967
     1754587.286      433503.305     1754315.366      434163.148
     1754744.578      435059.207     1754369.578        435743.4
     1754671.429      437084.143     1755183.909      437783.654
     1755455.546      438671.459     1755424.183      440261.878
     1756158.724      442021.933     1757642.147      442678.999
     1757251.272        443526.4     1757524.092      443817.888
      1758114.37      443738.027     1758644.753      443183.522
     1759296.661      443399.485     1760099.896      444906.935

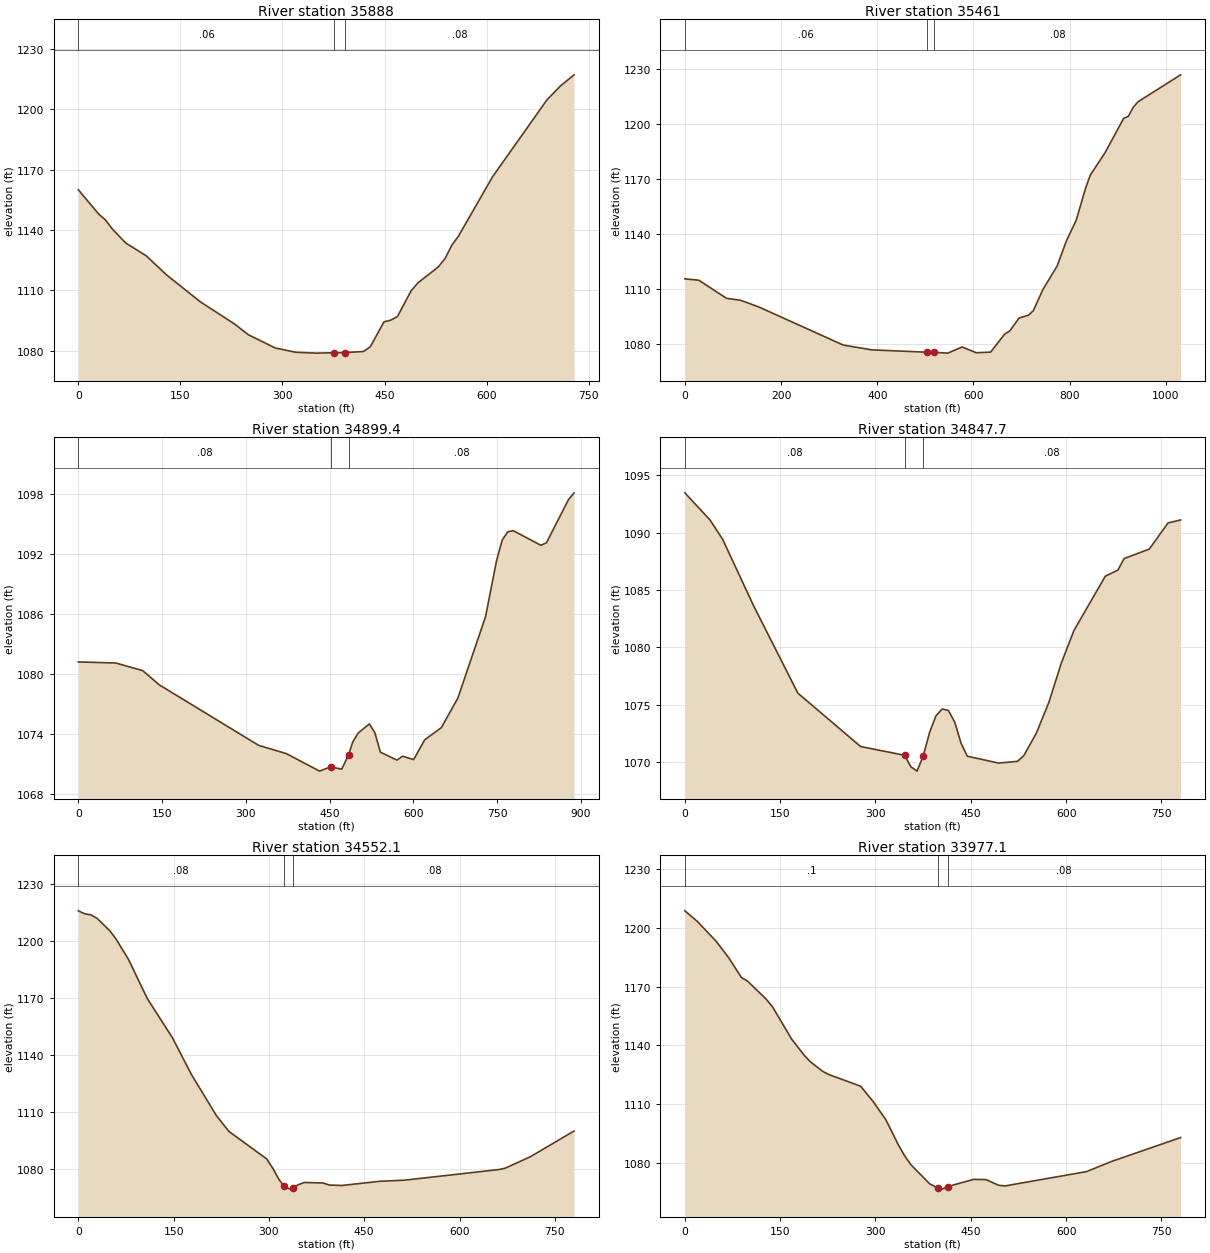
Type RM Length L Ch R = 1 ,35888   ,431.4,427,421
XS GIS Cut Line= 2
     1752780.761      418286.165     1753389.245      418686.686
#Sta/Elev= 30
       0 1159.97    29.9 1147.91    39.9    1145    49.9 1140.53    69.8 1133.51
    99.8 1127.21   129.7 1117.72   179.6  1104.3   229.5  1093.4   249.5 1088.11
   289.4 1081.47   319.3 1079.37   349.3 1078.92   376.3 1079.12   391.3 1079.19
   419.1 1079.73   429.1  1082.1   449.1 1094.42     459 1095.28     469 1097.08
     489 1109.82     499 1113.78   528.9 1121.66   538.9 1125.87   548.8 1132.43
   558.8 1137.09   608.7 1166.39   688.6 1204.55   708.5 1211.47   728.5 1216.99
#Mann= 3 , 0 , 0
       0     .06       0   376.3    .045       0   391.3     .08       0
Bank Sta=376.3,391.3
XS Rating Curve= 0 ,0
Exp/Cntr=0.3,0.1

Type RM Length L Ch R = 1 ,35461   ,538,561.6,549.9
XS GIS Cut Line= 3
     1752356.136       418621.52     1752590.147      418710.667
     1753319.313      418988.445
#Sta/Elev= 30
       0 1115.76    28.9 1115.02    86.7 1105.14   115.6 1104.12   154.1  1100.4
   329.4 1079.67   388.7 1077.07   503.4 1075.79   518.4 1075.74   546.7 1075.29
   576.4 1078.64     606  1075.5   635.6 1075.84   665.2 1085.76   675.1 1087.26
   694.9 1094.42   714.6 1095.97   724.5 1098.46   744.3 1109.91   773.9 1122.72
   793.6 1136.72   813.4 1147.53   833.2 1165.24     843 1172.34   872.7  1184.1
   912.2 1203.14     922 1204.32   931.9 1209.12   941.8 1212.17  1030.7 1226.91
#Mann= 3 , 0 , 0
       0     .06       0   503.4    .045       0   518.4     .08       0
Bank Sta=503.4,518.4
XS Rating Curve= 0 ,0
Exp/Cntr=0.3,0.1

Type RM Length L Ch R = 1 ,34899.4 ,51.9,51.7,51.5
XS GIS Cut Line= 4
      1752366.64       418994.42     1752460.963      419041.554
     1752611.334      419116.696     1753184.338      419338.389
#Sta/Elev= 30
       0 1081.23    67.1 1081.12   115.3 1080.36     145 1078.94   323.1 1072.89
   372.6 1072.07   432.1 1070.32   451.9 1070.75   471.7 1070.51     484 1071.95
   491.6 1073.24   501.5 1074.14   521.3 1075.04   531.2 1074.14   541.1 1072.21
   570.8 1071.42   580.7 1071.81   600.6 1071.47   620.4 1073.45   650.1 1074.66
   679.8 1077.62   729.4 1085.76   749.2 1091.38   759.1 1093.39     769 1094.22
   778.9 1094.34   828.5 1092.88   838.4 1093.13     878 1097.45   887.9 1098.12
#Mann= 3 , 0 , 0
       0     .08       0   451.9    .045       0     484     .08       0
Bank Sta=451.9,484
XS Rating Curve= 0 ,0
Exp/Cntr=0.3,0.1

Type RM Length L Ch R = 1 ,34847.7 ,295.5,295.6,295.6
XS GIS Cut Line= 2
     1752441.966      419108.437     1753171.133      419386.214
#Sta/Elev= 30
       0 1093.46    39.5  1091.1    59.3 1089.43   108.6 1083.58   177.8 1076.03
   276.6 1071.38   345.7 1070.62   355.6 1069.63   365.4 1069.24   375.1 1070.55
   385.2 1072.61   395.1 1074.05     405 1074.65   414.8 1074.52   424.7 1073.51
   434.6 1071.69   444.5 1070.54   493.8 1069.94   523.5 1070.09   533.4 1070.58
   553.1 1072.53   572.9 1075.22   592.6 1078.66   612.4 1081.48   661.8 1086.21
   681.5 1086.73   691.4 1087.74   730.9 1088.56   760.5 1090.84   780.3  1091.1
#Mann= 3 , 0 , 0
       0     .08       0   345.7    .045       0   375.1     .08       0
Bank Sta=345.7,375.1
XS Rating Curve= 0 ,0
Exp/Cntr=0.3,0.1

Type RM Length L Ch R = 1 ,34552.1 ,571,575,579.4
XS GIS Cut Line= 2
     1752388.684       419403.57      1753117.85      419681.348
#Sta/Elev= 30
       0 1215.87     9.9 1214.33    19.8 1213.74    29.6  1211.9    49.4 1205.45
    59.3 1201.11      79 1190.32   108.6 1169.74   148.2 1149.18   177.8 1130.02
   217.3 1108.33     237 1100.02   296.3  1085.6   306.2  1080.6   316.1  1074.6
   323.4 1071.49   325.9 1070.43   335.8 1069.69   338.4 1070.28   345.7 1071.94
   355.6 1073.19   385.2 1072.92   395.1 1071.84   414.8  1071.6   474.1  1073.8
   513.6  1074.4   661.8 1079.97   671.6 1080.65   711.2 1086.65   780.3 1100.22
#Mann= 3 , 0 , 0
       0     .08       0   323.4    .045       0   338.4     .08       0
Bank Sta=323.4,338.4
XS Rating Curve= 0 ,0
Exp/Cntr=0.3,0.1

Type RM Length L Ch R = 1 ,33977.1 ,248.2,241.3,227.8
XS GIS Cut Line= 2
     1752159.783      419849.872      1752827.58       420253.47
#Sta/Elev= 30
       0 1208.72    19.8 1203.24    49.4 1193.07    69.1 1184.69    88.9 1174.66
    98.8 1172.74   128.4 1163.41   138.3 1159.45   167.9  1143.2   187.7 1134.91
   197.5 1131.54   217.3 1126.55   227.2 1124.92   276.6 1119.06   296.3  1111.2
   316.1 1102.05   335.8 1089.19   345.7 1083.57   355.6 1078.95   385.2 1069.16
   398.9 1066.84     405 1066.41   413.9 1067.74   454.3 1071.39   474.1 1071.29
   493.8 1068.39   503.7 1068.04   632.1 1075.36   671.6 1080.56   780.3 1092.78
#Mann= 3 , 0 , 0
       0      .1       0   398.9    .045       0   413.9     .08       0
#XS Ineff= 2 , 0
                          455.62         1071.22
Permanent Ineff=
       F       F
Bank Sta=398.9,413.9
XS Rating Curve= 0 ,0
Exp/Cntr=0.3,0.1

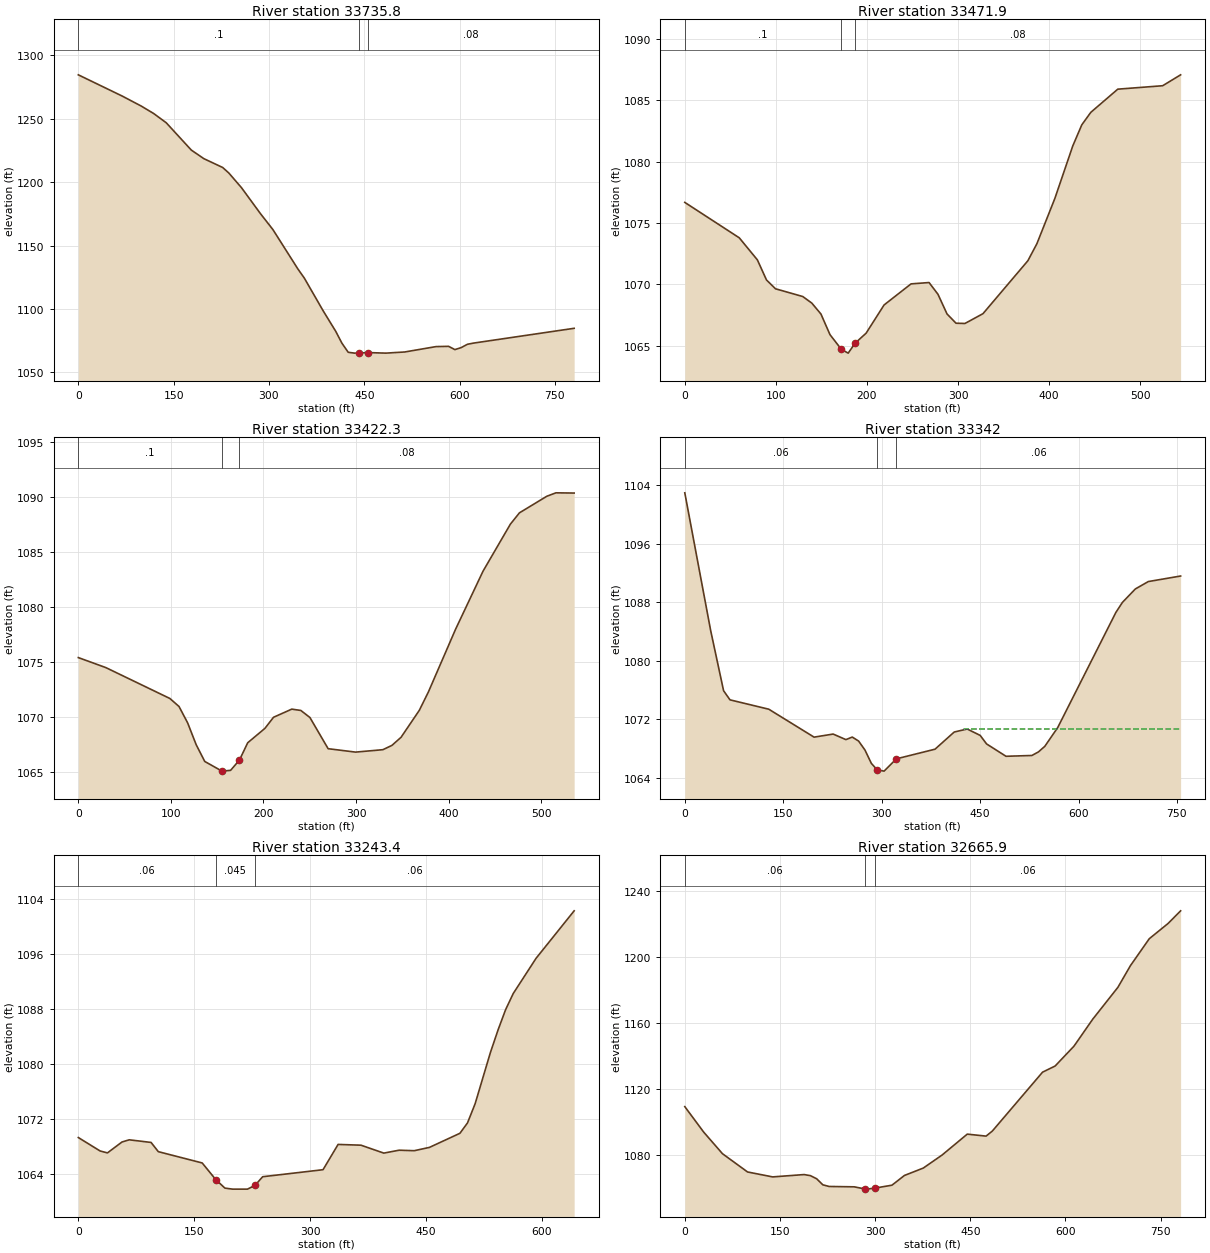
Type RM Length L Ch R = 1 ,33735.8 ,285.4,263.9,255.9
XS GIS Cut Line= 2
     1751963.263      420091.264     1752692.429      420369.042
#Sta/Elev= 30
       0 1284.74    69.1 1267.97    98.8 1260.15   118.5 1254.24   138.3 1246.94
   177.8 1225.37   197.5 1218.61   227.2 1211.62     237 1207.19   256.8 1195.67
   286.4 1175.36   306.2 1162.65   345.7 1131.43   355.6 1124.41   385.2 1098.63
     405 1082.44   414.8 1073.03   424.7 1065.84   434.6 1065.16   441.4 1065.26
   456.4 1065.58     484 1065.16   513.6 1066.06     563 1070.32   582.7 1070.51
   592.6 1067.94   602.5 1069.51   612.4 1072.15   622.2 1073.09   780.3 1084.75
#Mann= 3 , 0 , 0
       0      .1       0   441.4    .045       0   456.4     .08       0
#XS Ineff= 2 , 0
                          573.96         1070.09
Permanent Ineff=
       F       F
Bank Sta=441.4,456.4
XS Rating Curve= 0 ,0
Exp/Cntr=0.3,0.1

Type RM Length L Ch R = 1 ,33471.9 ,66.7,49.6,45.2
XS GIS Cut Line= 3
     1752225.254       420592.74     1752366.673      420482.433
     1752720.007      420390.585
#Sta/Elev= 30
       0 1076.68    59.8 1073.79    79.7 1071.99    89.7 1070.35    99.6 1069.63
   129.5    1069   139.5 1068.46   149.5 1067.57   159.4 1065.89     172 1064.68
   179.4 1064.38     187 1065.19   199.1 1066.01   218.8 1068.31   248.4 1070.03
   268.2 1070.14     278 1069.18   287.9 1067.58   297.8 1066.82   307.6  1066.8
   327.4  1067.6   376.7 1071.92   386.6 1073.31   406.3    1077     426 1081.29
   435.9 1083.01   445.8 1084.03   475.4 1085.92   524.7  1086.2   544.4 1087.09
#Mann= 3 , 0 , 0
       0      .1       0     172    .045       0     187     .08       0
#XS Ineff= 2 , 0
                          259.88         1070.03
Permanent Ineff=
       F       F
Bank Sta=172,187
XS Rating Curve= 0 ,0
Exp/Cntr=0.3,0.1

Type RM Length L Ch R = 1 ,33422.3 ,76.7,80.2,56.8
XS GIS Cut Line= 4
     1752241.514      420628.308     1752322.377      420555.551
     1752414.825      420512.213     1752728.998       420429.74
#Sta/Elev= 30
       0 1075.39    29.7 1074.48    98.9 1071.67   108.8 1070.94   118.1 1069.45
   127.3 1067.47   136.6 1065.94   155.2 1065.06   164.5 1065.13   174.1 1066.07
     183 1067.64   201.6 1068.95   210.9 1069.96   230.6  1070.7   240.4 1070.58
   250.2 1069.94   269.9  1067.1   299.5 1066.79     329 1067.01   338.8  1067.4
   348.7 1068.14   368.4 1070.59   378.2 1072.26   407.7 1077.99   437.3 1083.26
   466.8 1087.53   476.6 1088.56   506.2 1090.07     516 1090.38   535.7 1090.36
#Mann= 3 , 0 , 0
       0      .1       0   155.2    .045       0   174.1     .08       0
#XS Ineff= 2 , 0
                          231.71         1070.66
Permanent Ineff=
       F       F
Bank Sta=155.2,174.1
XS Rating Curve= 0 ,0
Exp/Cntr=0.3,0.1

Type RM Length L Ch R = 1 ,33342   ,111,98.6,96.6
XS GIS Cut Line= 5
     1752128.453      420711.594     1752324.802      420695.768
      1752392.69      420524.366     1752410.485      420516.553
     1752755.036      420431.712
#Sta/Elev= 30
       0 1102.95    39.4 1084.12    59.1 1075.88    68.9 1074.63     128 1073.35
     197 1069.53   226.1 1069.95   245.5 1069.19   255.2 1069.54   264.9 1068.99
   274.6 1067.76   284.3 1065.94   293.3 1065.05   303.7 1064.88   322.41066.559
   381.3 1067.88   410.6 1070.23   430.4 1070.64   450.1 1069.77   459.9  1068.6
   489.5 1066.91   528.9 1067.02   538.8  1067.5   548.6 1068.27   568.3 1070.84
     657  1086.6   666.9 1087.96   686.6  1089.8   706.3 1090.81   755.6 1091.57
#Mann= 3 , 0 , 0
       0     .06       0   293.3    .045       0   322.4     .06       0
#XS Ineff= 2 , 0
                          425.15         1070.59
Permanent Ineff=
       F       F
Bank Sta=293.3,322.4
XS Rating Curve= 0 ,0
Exp/Cntr=0.3,0.1

Type RM Length L Ch R = 1 ,33243.4 ,530.4,577.5,613.5
XS GIS Cut Line= 4
     1752292.661      420761.547     1752428.772      420696.964
       1752475.3      420517.103     1752780.198      420496.015
#Sta/Elev= 30
       0 1069.31    28.2 1067.36    37.7 1067.08    56.5 1068.66    65.9 1068.98
    94.2  1068.6   103.6 1067.26   160.4 1065.62     1781063.203   189.8 1061.97
   199.6 1061.82   219.1 1061.82   228.9 1062.37   238.7 1063.62   316.9 1064.64
   336.4 1068.31     366  1068.2   395.6 1067.05   415.3 1067.47     435  1067.4
   454.7 1067.88   494.2 1069.93     504 1071.44   513.9 1074.23   533.6 1081.64
   543.5 1084.92   553.3 1087.87   563.2 1090.22   592.8 1095.34   642.1 1102.23
#Mann= 3 , 0 , 0
       0     .06       0     178    .045       0   228.9     .06       0
Bank Sta=178,228.9
XS Rating Curve= 0 ,0
Exp/Cntr=0.3,0.1

Type RM Length L Ch R = 1 ,32665.9 ,468.8,471.1,460.3
XS GIS Cut Line= 2
     1752135.116      420848.658     1752894.384       421033.92
#Sta/Elev= 30
       0 1109.41    29.7 1093.99    59.4 1080.85    98.9 1069.78   138.5 1066.78
     188  1068.2   197.9 1067.56   207.8 1065.66   217.6 1061.98   227.5 1060.98
   267.1 1060.76     2841059.465   286.9 1059.37   299.91060.016   326.5 1061.75
   346.2 1067.66   375.9 1072.14   405.6 1080.07   445.2 1092.72   474.9 1091.52
   484.8 1094.62   563.9 1130.31   583.7 1134.03   613.4 1146.08     643 1162.45
   682.6 1181.74   702.4 1194.91   732.1 1211.24   761.8 1220.52   781.5 1228.16
#Mann= 3 , 0 , 0
       0     .06       0     284    .045       0   299.9     .06       0
Bank Sta=284,299.9
XS Rating Curve= 0 ,0
Exp/Cntr=0.3,0.1

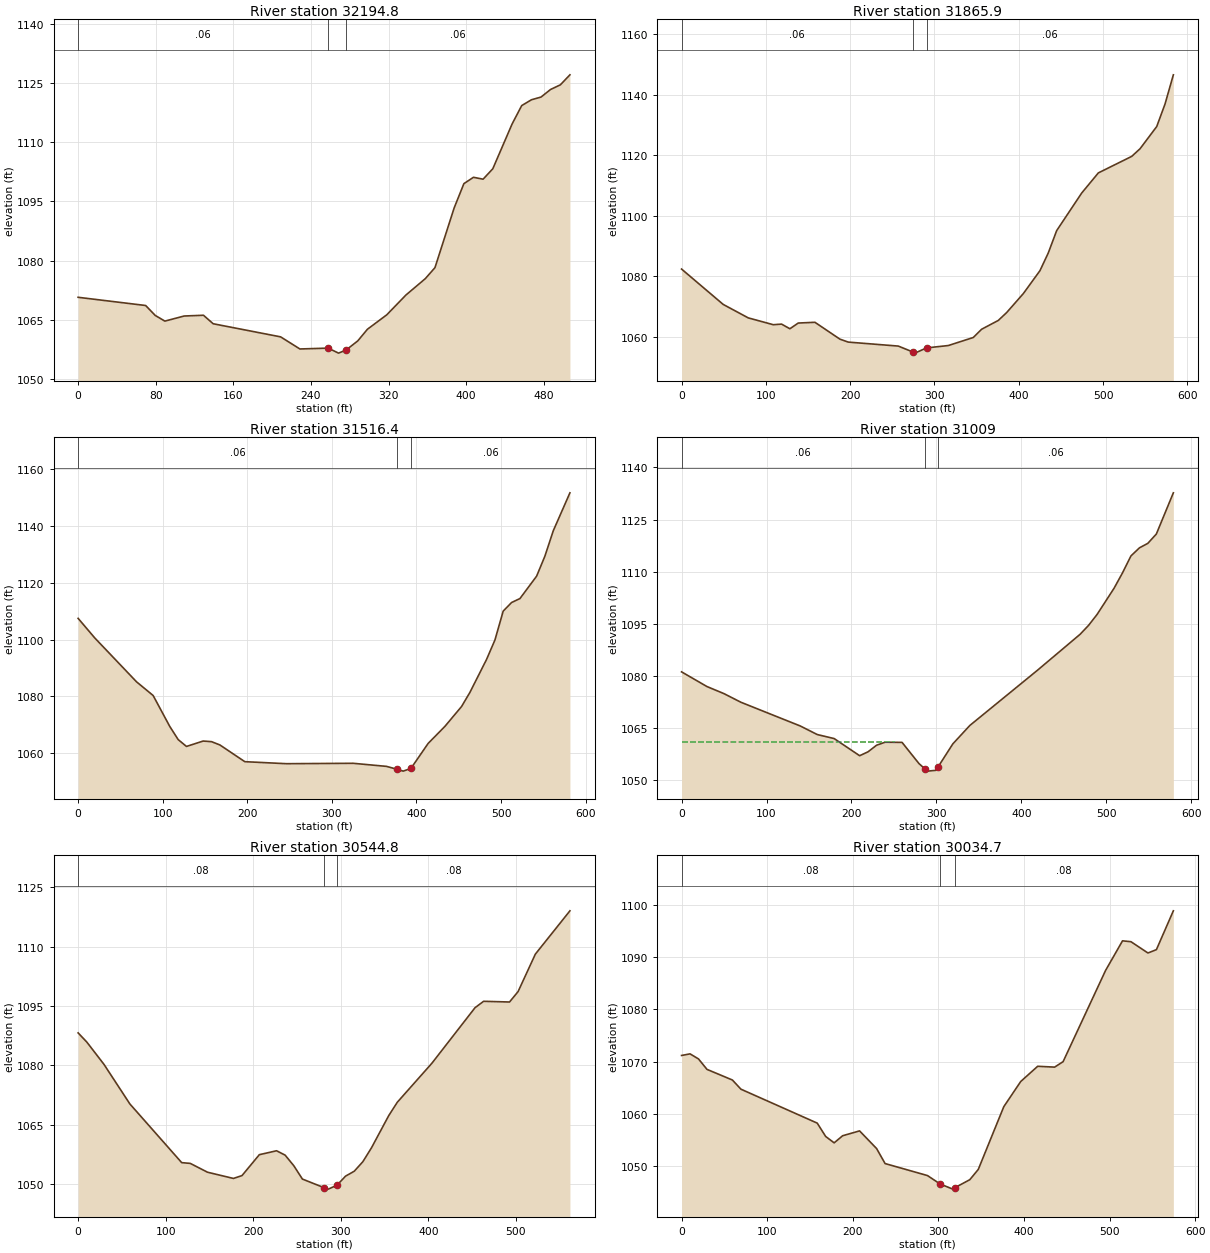
Type RM Length L Ch R = 1 ,32194.8 ,324.8,328.9,323.7
XS GIS Cut Line= 2
     1752157.418      421307.442     1752664.274      421300.181
#Sta/Elev= 30
       0 1070.71    69.6 1068.63    79.5 1066.11    89.4 1064.68   109.3 1065.97
   129.2 1066.16   139.2 1064.01   208.7 1060.69   228.6 1057.62   257.71057.839
   268.4 1056.57   276.2 1057.36   288.2 1059.66   298.2 1062.62   318.1 1066.27
   337.9 1071.29   357.8 1075.42   367.8 1078.22   387.6 1093.36   397.6 1099.49
   407.5  1101.1   417.4 1100.62   427.4 1103.26   447.3  1114.6   457.2 1119.26
   467.2 1120.73   477.1 1121.42     487 1123.35     497 1124.51   506.9 1127.05
#Mann= 3 , 0 , 0
       0     .06       0   257.7    .045       0   276.2     .06       0
Bank Sta=257.7,276.2
XS Rating Curve= 0 ,0
Exp/Cntr=0.3,0.1

Type RM Length L Ch R = 1 ,31865.9 ,354,349.5,343.7
XS GIS Cut Line= 2
     1752174.155      421651.749     1752732.629      421483.322
#Sta/Elev= 30
       0 1082.35    49.4 1070.65    79.1  1066.2   108.8 1063.94   118.6 1064.14
   128.5  1062.6   138.4 1064.49   158.2 1064.74   187.8 1059.17   197.7 1058.19
   257.1 1056.87   274.51054.896   276.8 1054.54   290.61056.271   316.4 1057.05
     346 1059.71   355.9 1062.44   375.7 1065.36   385.6 1067.96   405.4 1074.25
   425.1 1081.82     435 1087.71   444.9 1095.06   474.6  1107.5   494.3 1114.15
   533.9 1119.62   543.8 1122.15   563.6  1129.5   573.4 1136.92   583.3  1146.6
#Mann= 3 , 0 , 0
       0     .06       0   274.5    .045       0   290.6     .06       0
Bank Sta=274.5,290.6
XS Rating Curve= 0 ,0
Exp/Cntr=0.3,0.1

Type RM Length L Ch R = 1 ,31516.4 ,507.4,507.3,505.2
XS GIS Cut Line= 2
     1752304.529       421992.52     1752828.779       421740.93
#Sta/Elev= 30
       0 1107.46    19.7 1100.55      69 1085.11    88.7 1080.26   108.4 1069.34
   118.3 1064.73   128.1 1062.31   147.8 1064.21   157.7    1064   167.6 1062.84
   197.1 1056.94   246.4 1056.23   325.2 1056.37   364.7 1055.28   377.41054.236
   384.4 1053.61   393.51054.565   413.9 1063.39   433.7 1069.39   453.4  1076.4
   463.2 1081.34   482.9 1092.97   492.8 1099.81   502.6 1110.02   512.5 1113.04
   522.4 1114.44   542.1 1122.33   551.9 1129.38   561.8 1138.33   581.5 1151.71
#Mann= 3 , 0 , 0
       0     .06       0   377.4    .045       0   393.5     .06       0
Bank Sta=377.4,393.5
XS Rating Curve= 0 ,0
Exp/Cntr=0.3,0.1

Type RM Length L Ch R = 1 ,31009   ,467.8,464.3,460.7
XS GIS Cut Line= 2
     1752472.561      422421.934     1752977.094      422138.303
#Sta/Elev= 30
       0 1081.12    29.9 1076.89    49.9 1074.85    69.8 1072.37   139.7 1065.53
   159.7 1063.06   179.6  1061.9   209.6 1056.96   219.5 1058.09   229.5 1059.98
   239.5 1060.85   259.5  1060.8   279.4  1054.7   286.5 1053.15   289.4 1052.52
   299.4 1052.75   301.61053.619   319.3 1060.38   339.3 1065.68   419.1 1081.63
     469 1091.93     479 1094.51     489 1097.65   508.9 1105.16   518.9 1109.61
   528.9 1114.52   538.9 1116.85   548.8 1118.15   558.8 1120.84   578.8  1132.7
#Mann= 3 , 0 , 0
       0     .06       0   286.5    .045       0   301.6     .06       0
#XS Ineff= 2 , 0
          250.84 1061.05
Permanent Ineff=
       F       F
Bank Sta=286.5,301.6
XS Rating Curve= 0 ,0
Exp/Cntr=0.3,0.1

Type RM Length L Ch R = 1 ,30544.8 ,503.5,510,461.4
XS GIS Cut Line= 2
     1752777.842      422828.749     1753217.755      422479.395
#Sta/Elev= 30
       0 1088.23     9.9 1085.92    29.6 1080.26    59.1 1070.29   118.3 1055.46
   128.1 1055.27   147.8 1053.04   177.4 1051.47   187.2 1052.19     207 1057.47
   226.7 1058.46   236.5 1057.35   246.4 1054.67   256.2 1051.31   280.61049.167
   285.8 1048.77   295.7 1049.76   305.5 1052.05   315.4 1053.29   325.2 1055.68
   335.1  1059.2   354.8 1067.33   364.6 1070.71   404.1 1080.56   453.4 1094.59
   463.2 1096.21   492.8 1096.03   502.6 1098.67   522.3 1108.12   561.8 1119.06
#Mann= 3 , 0 , 0
       0     .08       0   280.6    .045       0   295.7     .08       0
#XS Ineff= 2 , 0
           226.4 1058.37
Permanent Ineff=
       F       F
Bank Sta=280.6,295.7
XS Rating Curve= 0 ,0
Exp/Cntr=0.3,0.1

Type RM Length L Ch R = 1 ,30034.7 ,516.5,534.5,484.7
XS GIS Cut Line= 2
     1753001.413      423124.932     1753451.387      422767.588
#Sta/Elev= 30
       0 1071.16     9.9 1071.47    19.8  1070.5    29.7  1068.5    59.4 1066.46
    69.4  1064.7   158.5  1058.2   168.4 1055.64   178.3 1054.42   188.2 1055.78
     208 1056.71   227.9 1053.32   237.8 1050.45   287.3 1048.15   302.21046.524
     317 1045.55   319.41045.829   336.8 1047.36   346.7 1049.33   376.5 1061.35
   396.3 1066.18   416.1 1069.09   435.9 1068.93   445.8 1069.98   495.4 1087.45
   515.2 1093.13   525.1 1092.96   544.9  1090.8   554.8 1091.44   574.6 1098.88
#Mann= 3 , 0 , 0
       0     .08       0   302.2    .045       0   319.4     .08       0
Bank Sta=302.2,319.4
XS Rating Curve= 0 ,0
Exp/Cntr=0.3,0.1

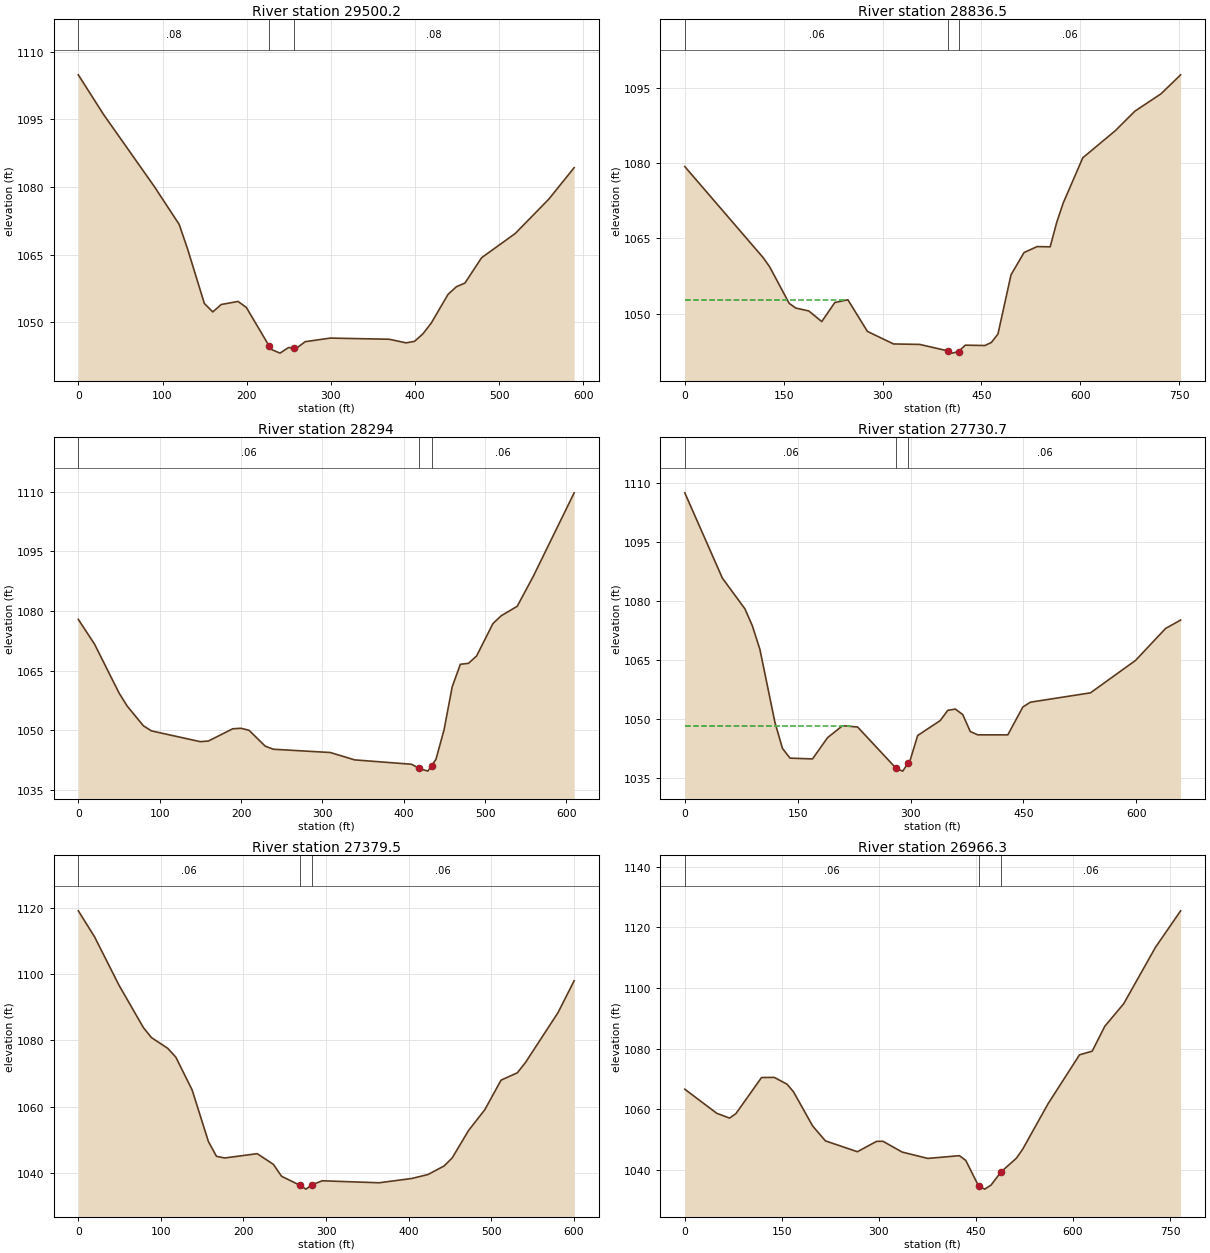
Type RM Length L Ch R = 1 ,29500.2 ,619.9,663.7,669.4
XS GIS Cut Line= 2
     1753244.985      423447.614     1753688.992      423060.682
#Sta/Elev= 30
       0 1104.89      30 1096.08    89.8 1080.22   119.8 1071.69   129.8 1066.22
   149.7 1054.14   159.7 1052.26   169.7  1053.9   189.7 1054.59   199.6 1053.25
   226.71044.686   229.6  1043.9   239.6 1043.11   249.6 1044.34   255.71044.285
   259.5 1044.25   269.5 1045.65   299.5 1046.45   369.3 1046.19   389.3 1045.39
   399.3 1045.72   409.3 1047.38   419.2 1049.77   439.2 1056.16   449.2 1057.86
   459.2 1058.65   479.1  1064.3   519.1 1069.68     559 1077.32     589 1084.28
#Mann= 3 , 0 , 0
       0     .08       0   226.7    .045       0   255.7     .08       0
Bank Sta=226.7,255.7
XS Rating Curve= 0 ,0
Exp/Cntr=0.3,0.1

Type RM Length L Ch R = 1 ,28836.5 ,483.9,542.5,548.2
XS GIS Cut Line= 2
     1753383.524      423768.117     1754120.245      423616.187
#Sta/Elev= 30
       0 1079.34   118.8 1061.18   128.7 1059.34   158.4 1052.03   168.3  1051.1
   188.1 1050.52   207.8  1048.4   227.6  1052.2   247.4 1052.75   277.1 1046.43
   316.7 1043.93   356.3 1043.84   399.51042.537   405.8  1042.1   415.31042.415
   425.6 1043.69   455.3 1043.62   465.2 1044.24   475.1 1045.92   494.9 1057.74
   514.7 1062.18   534.5 1063.37   554.3 1063.32   564.2  1068.2   574.1 1072.08
   603.8  1081.1   653.2 1086.52   682.9 1090.41   722.5 1093.88   752.2 1097.66
#Mann= 3 , 0 , 0
       0     .06       0   399.5    .045       0   415.3     .06       0
#XS Ineff= 2 , 0
          245.88 1052.78
Permanent Ineff=
       F       F
Bank Sta=399.5,415.3
XS Rating Curve= 0 ,0
Exp/Cntr=0.3,0.1

Type RM Length L Ch R = 1 ,28294   ,558,563.3,567.8
XS GIS Cut Line= 2
     1753501.697      424049.914     1754111.169      424051.812
#Sta/Elev= 30
       0 1077.88      20 1071.62      50 1059.37      60 1056.07    79.9  1051.1
    89.9  1049.8   149.9 1047.09   159.9 1047.25   189.8 1050.33   199.8 1050.46
   209.8 1049.96   229.8 1045.95   239.8 1045.18   309.7 1044.36   339.7  1042.5
   409.6  1041.4   419.11040.351   429.6 1039.67   434.2 1041.03   439.6 1042.63
   449.6 1050.11   459.6 1060.92   469.6 1066.57   479.6 1066.82   489.6 1068.68
   509.6  1076.8   519.6 1078.76   539.5 1081.18   559.5 1088.82   609.5 1109.75
#Mann= 3 , 0 , 0
       0     .06       0   419.1    .045       0   434.2     .06       0
Bank Sta=419.1,434.2
XS Rating Curve= 0 ,0
Exp/Cntr=0.3,0.1

Type RM Length L Ch R = 1 ,27730.7 ,347.3,351.2,354.7
XS GIS Cut Line= 2
     1753445.571      424440.171     1754088.051      424585.939
#Sta/Elev= 30
       0 1107.55    49.9 1085.84    79.9    1078    89.8 1073.66    99.8 1067.67
   119.8 1049.05   129.8 1042.44   139.8 1039.97   169.7 1039.77   189.7 1045.19
   209.6 1048.23   229.6  1047.9     2811037.333   289.5 1036.66   296.71038.693
   299.5 1039.48   309.4 1045.73   339.4 1049.54   349.4 1052.14   359.4 1052.47
   369.3 1051.07   379.3 1046.75   389.3  1045.9   429.2  1045.9   449.2    1053
   459.2 1054.22     539  1056.6   598.9 1064.86   638.8    1073   658.8 1075.14
#Mann= 3 , 0 , 0
       0     .06       0     281    .045       0   296.7     .06       0
#XS Ineff= 2 , 0
          221.35 1048.06
Permanent Ineff=
       F       F
Bank Sta=281,296.7
XS Rating Curve= 0 ,0
Exp/Cntr=0.3,0.1

Type RM Length L Ch R = 1 ,27379.5 ,419.6,413.2,406.8
XS GIS Cut Line= 2
     1753387.977      424742.541     1753947.119      424961.411
#Sta/Elev= 30
       0 1119.13    19.7 1111.26    49.2 1096.68    78.8 1083.85    88.6 1080.82
   108.3 1077.58   118.1 1074.91   137.8 1065.01   157.5 1049.44   167.3 1044.96
   177.2 1044.46   216.6 1045.76   236.2 1042.53   246.1 1038.93   267.91036.267
   275.6 1035.05   283.41036.394   295.3 1037.57   364.2 1036.97   403.6 1038.26
   423.3 1039.45     443 1042.06   452.8 1044.51   472.5 1052.76   492.2 1059.04
   511.9 1067.98   531.6 1070.19   541.4 1073.29   580.8 1088.35   600.4 1098.01
#Mann= 3 , 0 , 0
       0     .06       0   267.9    .045       0   283.4     .06       0
Bank Sta=267.9,283.4
XS Rating Curve= 0 ,0
Exp/Cntr=0.3,0.1

Type RM Length L Ch R = 1 ,26966.3 ,1442.7,1448.7,1454.3
XS GIS Cut Line= 3
     1753091.888      425143.395     1753476.079      425236.162
     1753845.709      425270.251
#Sta/Elev= 30
       0 1066.58    49.4 1058.64    69.2 1057.06      79 1058.53   118.6 1070.43
   138.3 1070.48   158.1 1068.23     168 1065.74   197.6 1054.47   217.4 1049.54
   266.8 1045.97   296.4 1049.38   306.3 1049.41     336 1045.85   375.5 1043.76
   424.5 1044.66   434.3  1043.1   454.11034.667   463.6 1033.63   473.4 1034.97
   488.91039.335   512.4 1043.79   522.2 1046.77   561.3 1061.72   610.1 1077.92
   629.7 1079.12   649.2 1087.33   678.5  1094.8   727.4 1113.34   766.4 1125.41
#Mann= 3 , 0 , 0
       0     .06       0   454.1    .045       0   488.9     .06       0
Bank Sta=454.1,488.9
XS Rating Curve= 0 ,0
Exp/Cntr=0.3,0.1

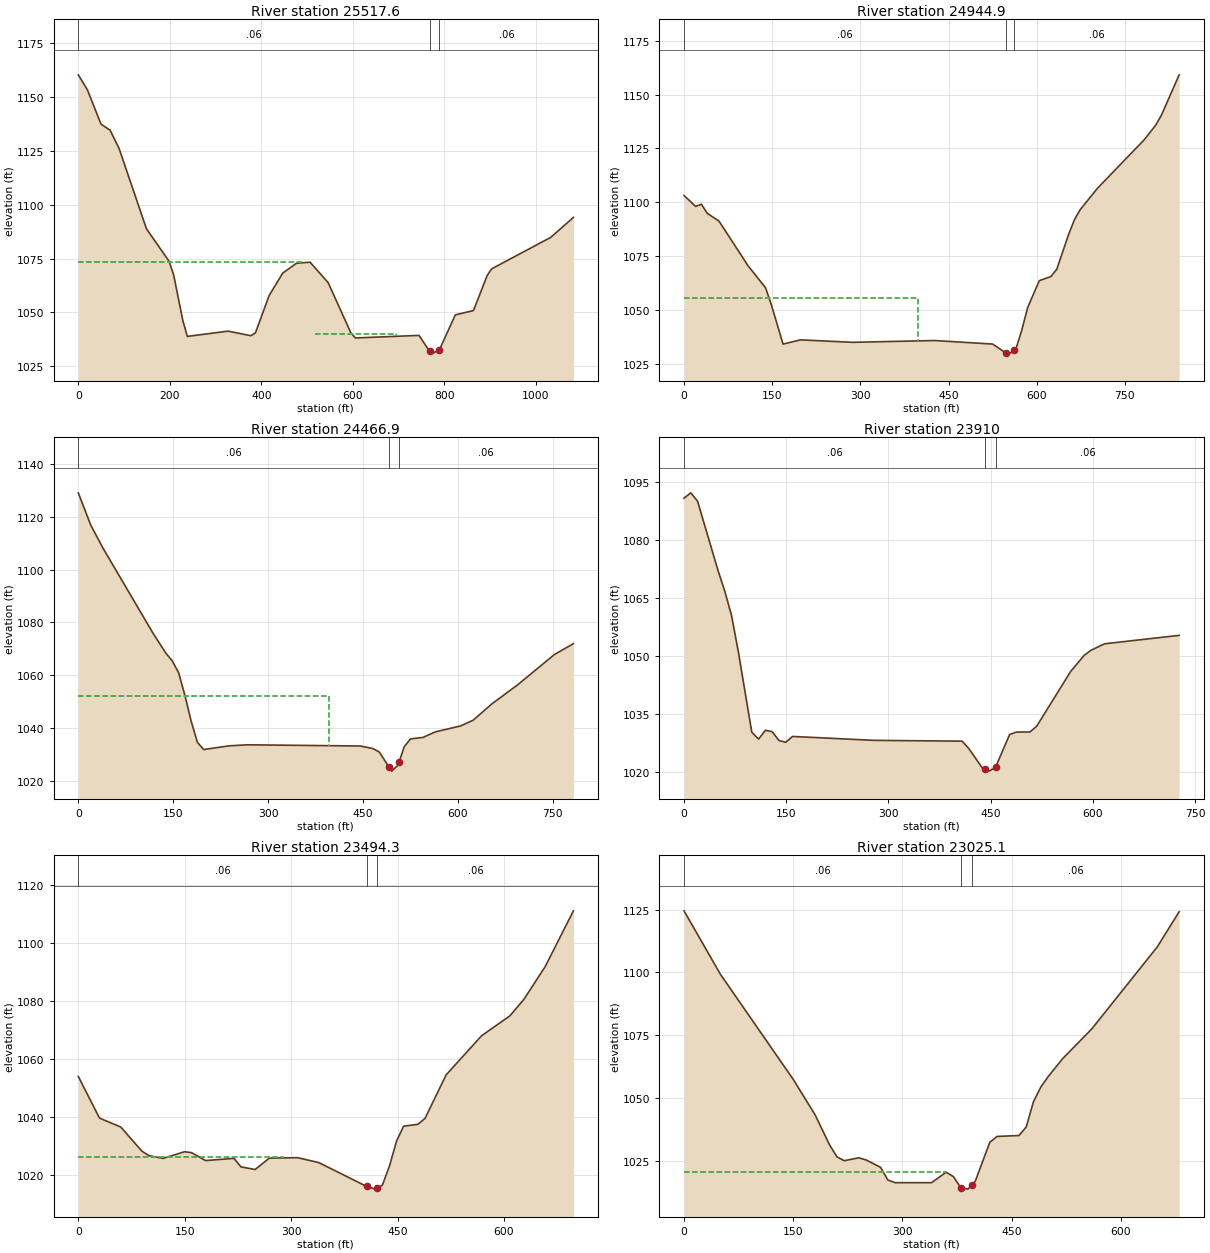
Type RM Length L Ch R = 1 ,25517.6 ,572.5,572.7,572.5
XS GIS Cut Line= 2
     1752954.662      426364.704     1753968.996      426741.412
#Sta/Elev= 30
       0 1160.37    19.8 1153.46    49.6 1137.48    69.5 1134.63    89.3 1126.05
   148.9 1088.84   198.5  1073.7   208.5 1067.28   228.3 1046.33   238.2 1038.81
   327.6 1041.26   377.2 1039.13   387.2 1040.49   416.9 1057.73   446.7 1068.21
   476.5 1072.78   506.3 1073.32     546 1063.81   595.6 1040.47   605.5 1038.09
   744.5 1039.28   767.51031.943   774.3 1031.04   788.91032.454   823.9 1048.82
   863.6 1050.82   893.4 1067.07   903.3  1070.2  1032.4 1084.83    1082 1094.12
#Mann= 3 , 0 , 0
       0     .06       0   767.5    .045       0   788.9     .06       0
#XS Ineff= 2 ,-1
       0  493.18 1073.27  516.56  695.13    1040
Permanent Ineff=
       F       F
Bank Sta=767.5,788.9
XS Rating Curve= 0 ,0
Exp/Cntr=0.3,0.1

Type RM Length L Ch R = 1 ,24944.9 ,477.2,478,478.8
XS GIS Cut Line= 2
     1752889.566      426944.062     1753679.217      427237.326
#Sta/Elev= 30
       0 1103.13    19.8 1098.06    29.7 1099.05    39.6 1094.83    59.5 1091.24
     109 1070.44   138.7 1060.25   148.6 1052.36   168.5 1034.04   198.2    1036
   287.4 1034.85   426.1 1035.69   525.2 1034.04   547.2 1029.97     555 1029.83
   562.2 1031.36   564.9 1031.93   574.8 1040.64   584.7 1051.02   604.5 1063.53
   624.3 1065.46   634.2 1068.82   654.1 1084.82     664  1091.7   673.9  1096.5
   703.6 1106.53   782.9 1129.02   802.7  1135.9   812.6 1140.66   842.4 1159.24
#Mann= 3 , 0 , 0
       0     .06       0   547.2    .045       0   562.2     .06       0
#XS Ineff= 2 , 0
          397.33 1055.38
Permanent Ineff=
       F       F
Bank Sta=547.2,562.2
XS Rating Curve= 0 ,0
Exp/Cntr=0.3,0.1

Type RM Length L Ch R = 1 ,24466.9 ,556.9,556.9,556.9
XS GIS Cut Line= 2
     1752741.426      427376.828     1753464.525      427675.951
#Sta/Elev= 30
       0 1129.04    19.8 1116.77    39.6 1107.86   118.9 1075.57   138.7 1068.25
   148.6 1065.39   158.5 1060.98   168.4 1052.45   178.3 1042.64   188.2  1034.6
   198.1 1031.84   237.7 1033.24   267.4 1033.65   445.7 1033.19   465.6 1032.22
   475.5 1030.96   491.61025.054   495.3 1023.68   505.2 1025.92   506.91027.121
   515.1 1032.92     525 1035.87   544.8 1036.45   564.6 1038.56   604.2 1040.79
     624 1042.95   653.8 1049.18   693.4 1056.18   752.8 1067.89   782.5 1071.93
#Mann= 3 , 0 , 0
       0     .06       0   491.6    .045       0   506.9     .06       0
#XS Ineff= 2 , 0
          396.71 1052.26
Permanent Ineff=
       F       F
Bank Sta=491.6,506.9
XS Rating Curve= 0 ,0
Exp/Cntr=0.3,0.1

Type RM Length L Ch R = 1 ,23910   ,414.8,415.7,416.5
XS GIS Cut Line= 2
     1752547.082      427897.168     1753218.548      428174.933
#Sta/Elev= 30
       0 1090.78      10 1092.16    19.9    1090    49.8 1072.15    59.7 1066.82
    69.7 1060.48    79.6  1051.2    99.5 1030.24   109.5 1028.48   119.4 1030.76
   129.4 1030.39   139.4 1028.11   149.3 1027.65   159.3 1029.16   278.7 1028.15
   408.1 1027.94   418.1    1026     438 1020.94   442.21020.618   447.9 1020.19
   457.3 1021.23   477.8 1029.64   487.8 1030.29   507.7 1030.32   517.6 1031.81
   567.4 1045.96   587.3 1050.14   597.2 1051.44   617.2 1053.12   726.6  1055.3
#Mann= 3 , 0 , 0
       0     .06       0   442.2    .045       0   457.3     .06       0
Bank Sta=442.2,457.3
XS Rating Curve= 0 ,0
Exp/Cntr=0.3,0.1

Type RM Length L Ch R = 1 ,23494.3 ,469.2,469.2,469.2
XS GIS Cut Line= 2
     1752407.122        428271.9     1753041.926      428561.934
#Sta/Elev= 30
       0 1054.01    29.9 1039.63    59.8 1036.56    89.7 1028.22    99.7 1026.68
   119.6 1025.73   149.6 1028.02   159.5 1027.72   179.5 1024.98   219.4 1025.74
   229.3  1022.8   249.3  1021.9   269.2 1025.82   309.1 1025.98     339 1024.28
   406.5 1016.05   418.8 1015.13   421.5 1015.52   428.7 1016.55   438.7 1023.16
   448.7  1031.8   458.6 1036.84   478.6 1037.48   488.6 1039.48   518.5 1054.54
   568.3    1068   608.2 1074.87   628.1 1080.59     658 1091.84   697.9 1111.12
#Mann= 3 , 0 , 0
       0     .06       0   406.5    .045       0   421.5     .06       0
#XS Ineff= 2 , 0
          288.93 1026.17
Permanent Ineff=
       F       F
Bank Sta=406.5,421.5
XS Rating Curve= 0 ,0
Exp/Cntr=0.3,0.1

Type RM Length L Ch R = 1 ,23025.1 ,426.9,424.6,422.1
XS GIS Cut Line= 2
     1752243.463      428710.084     1752861.925      428992.652
#Sta/Elev= 30
       0 1124.54      50 1099.26     150  1057.4     180 1043.31     200 1031.25
     210 1026.58     220    1025     240 1026.16     250 1025.31     270 1022.36
     280 1017.29     290 1016.25     340 1016.25     360 1020.41     370 1018.67
   380.11014.245     390 1013.68   395.31015.351     400 1016.83     420 1032.36
     430 1034.67     460 1035.03     470 1038.44     480 1048.54     490  1054.3
     500 1058.46     520 1065.65     560 1077.49     650 1110.18     680 1124.18
#Mann= 3 , 0 , 0
       0     .06       0   380.1    .045       0   395.3     .06       0
#XS Ineff= 2 , 0
          359.61 1020.36
Permanent Ineff=
       F       F
Bank Sta=380.1,395.3
XS Rating Curve= 0 ,0
Exp/Cntr=0.3,0.1