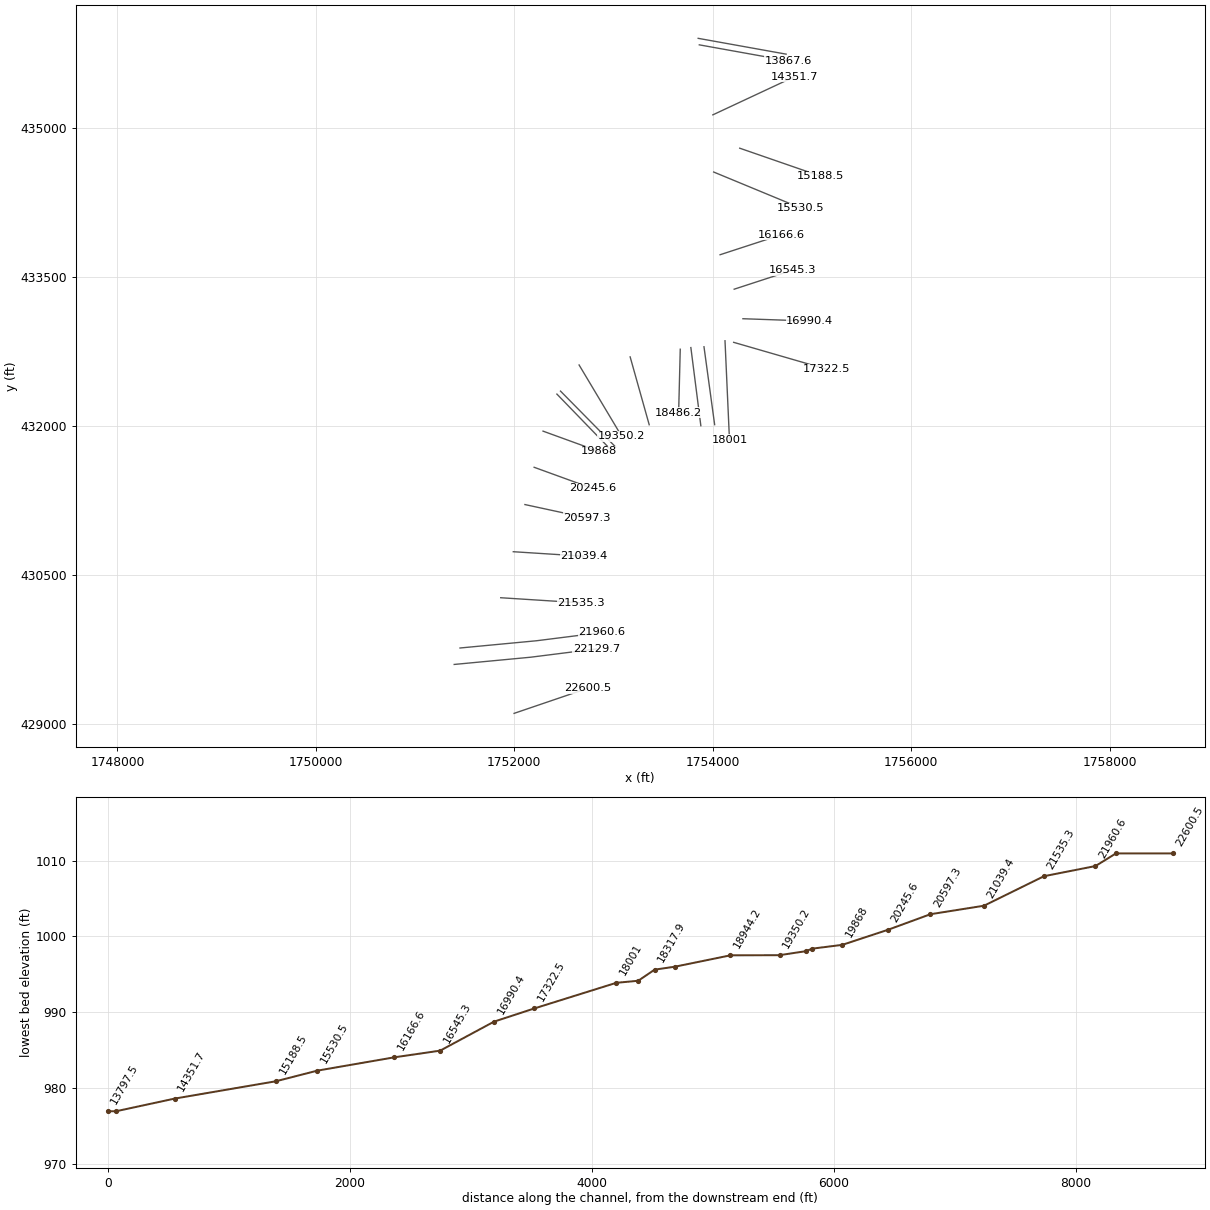
HEC-RAS study MiraclerRn.prj: MiraclerRn

--- MiraclerRn.g01 (geometry) --- (continued)

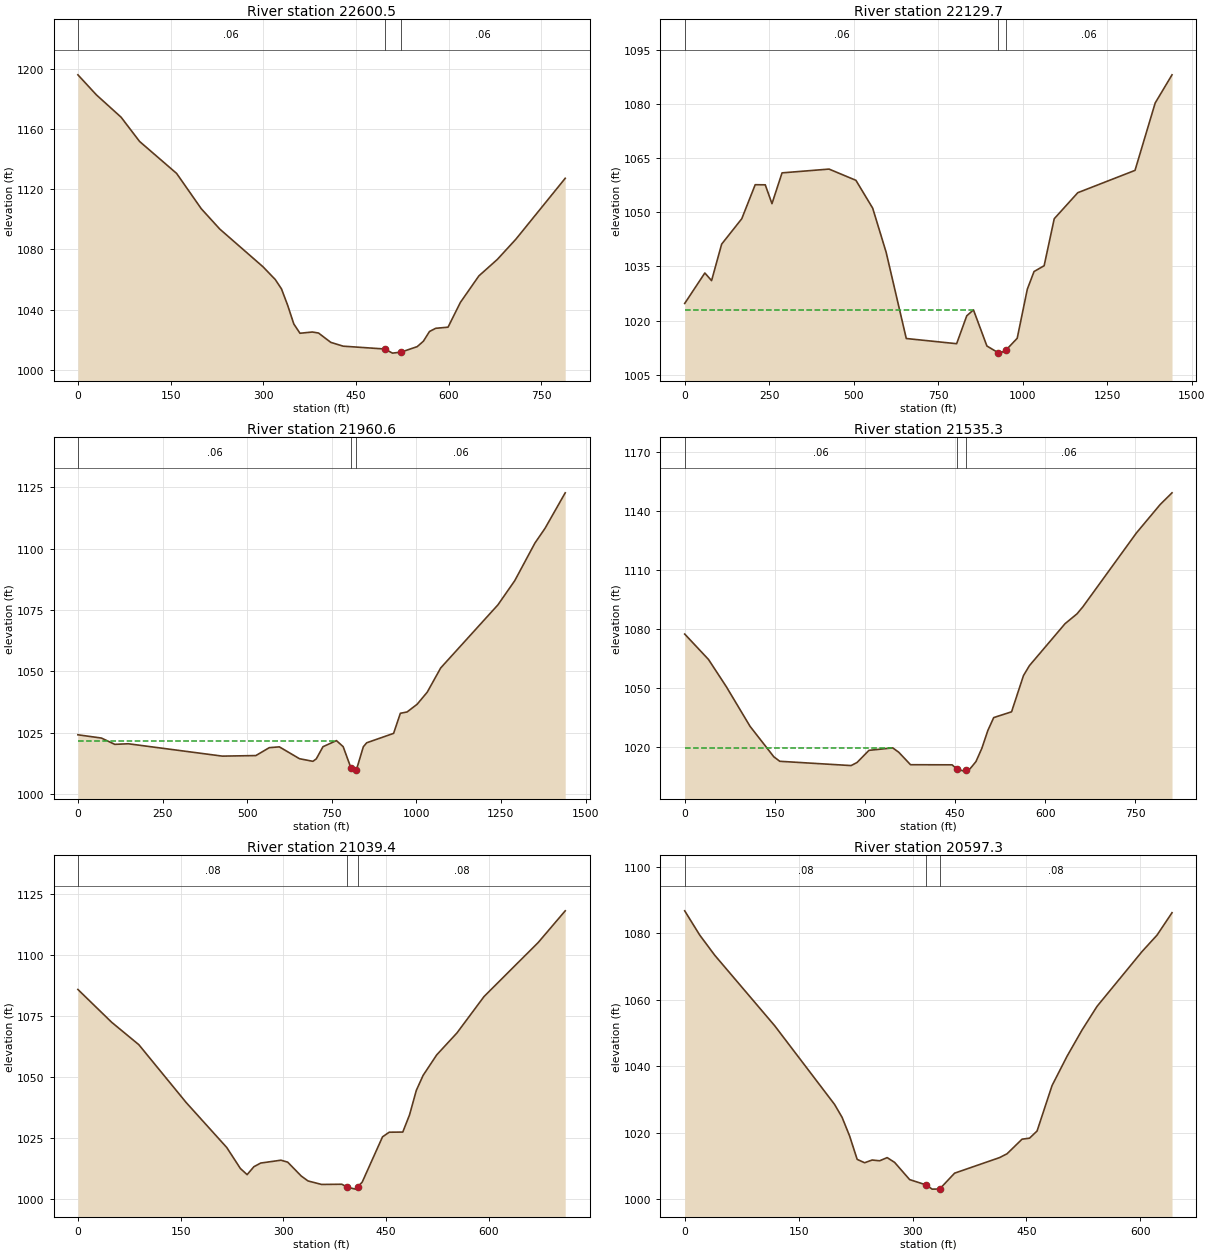
Type RM Length L Ch R = 1 ,22600.5 ,481.1,470.8,458.2
XS GIS Cut Line= 2
     1751997.328      429108.363     1752743.779      429362.426
#Sta/Elev= 30
       0  1196.3    29.9 1182.96    69.9 1168.07    99.8 1151.93   159.7 1130.65
   199.6 1107.14   229.6 1093.57   299.4 1068.51   319.4 1059.96   329.4 1053.74
   339.4 1042.84   349.3 1030.43   359.3  1024.2   379.3 1025.03   389.3 1024.36
   409.2 1018.13   429.2  1015.6   496.31013.725     509 1010.97     5231011.653
     549 1015.29   558.9 1018.86   568.9 1025.37   578.9  1027.5   598.9 1028.25
   618.8 1044.69   648.8  1062.4   678.7 1073.39   708.7 1086.85   788.5  1127.4
#Mann= 3 , 0 , 0
       0     .06       0   496.3    .045       0     523     .06       0
Bank Sta=496.3,523
XS Rating Curve= 0 ,0
Exp/Cntr=0.3,0.1

Type RM Length L Ch R = 1 ,22129.7 ,163.3,169.1,176.9
XS GIS Cut Line= 3
     1751393.902      429601.176     1752165.199      429674.136
     1752827.118      429757.528
#Sta/Elev= 30
       0 1024.73    59.6 1033.17    79.5 1031.05   109.3 1041.16   168.8 1048.19
   208.6 1057.62   238.4 1057.59   258.2 1052.37     288  1060.9   427.1 1061.95
   506.6 1058.84   556.2 1051.13     596 1038.92   655.6 1015.02   804.6 1013.58
   834.5  1021.3   854.4 1022.95   894.2 1012.94     9271011.117   934.1 1010.97
   951.11011.861   983.8 1015.08  1013.7 1028.66  1033.6 1033.57  1063.5 1035.18
  1093.4  1048.2  1163.1 1055.41  1332.4 1061.59  1392.1 1080.26  1441.9 1088.06
#Mann= 3 , 0 , 0
       0     .06       0     927    .045       0   951.1     .06       0
#XS Ineff= 2 , 0
          853.14 1022.96
Permanent Ineff=
       F       F
Bank Sta=927,951.1
XS Rating Curve= 0 ,0
Exp/Cntr=0.3,0.1

Type RM Length L Ch R = 1 ,21960.6 ,429,425.2,421
XS GIS Cut Line= 3
     1751452.491      429766.844     1752222.861      429839.717
     1752883.858      429922.992
#Sta/Elev= 30
       0 1024.12    69.4 1022.79   109.1 1020.22   148.8 1020.46   426.6 1015.42
   525.8 1015.64   565.5 1018.87   595.2  1019.2   654.8 1014.36   694.4  1013.3
   704.4  1014.3   724.2 1019.26   763.9 1021.75   783.8 1019.29   807.31010.418
   813.6  1009.3   822.51009.614   843.4 1019.23   853.4 1020.86   932.9  1024.7
   952.8 1032.88   972.7 1033.43  1002.5 1036.58  1032.3 1041.51  1072.1 1051.39
  1241.2 1077.12  1290.9 1086.98  1350.5 1102.32  1380.4 1108.33    1440  1122.8
#Mann= 3 , 0 , 0
       0     .06       0   807.3    .045       0   822.5     .06       0
#XS Ineff= 2 , 0
           766.7 1021.79
Permanent Ineff=
       F       F
Bank Sta=807.3,822.5
XS Rating Curve= 0 ,0
Exp/Cntr=0.3,0.1

Type RM Length L Ch R = 1 ,21535.3 ,496.2,496,495.7
XS GIS Cut Line= 2
     1751862.671      430273.097     1752671.959      430221.536
#Sta/Elev= 30
       0 1077.63    39.6 1064.72    69.2 1050.91   108.8  1030.7   148.3 1015.25
   158.2 1012.96   276.9 1010.78   286.8 1012.36   306.6 1018.52   346.1 1019.77
     356 1017.61   375.8 1011.22     445 1011.16   452.71009.054   464.8 1007.96
   468.81008.428   474.7 1009.11   484.6 1012.79   494.5 1019.58   504.4  1028.6
   514.2 1035.18   543.9 1038.11   563.7 1056.51   573.6 1061.57   632.9  1082.9
   652.7 1087.88   662.6  1091.5   751.6 1129.01   791.2 1143.48   810.9 1149.42
#Mann= 3 , 0 , 0
       0     .06       0   452.7    .045       0   468.8     .06       0
#XS Ineff= 2 , 0
          344.55  1019.8
Permanent Ineff=
       F       F
Bank Sta=452.7,468.8
XS Rating Curve= 0 ,0
Exp/Cntr=0.3,0.1

Type RM Length L Ch R = 1 ,21039.4 ,445.4,442.1,438.6
XS GIS Cut Line= 2
     1751989.515      430736.554     1752700.004      430691.287
#Sta/Elev= 30
       0 1085.93    49.4 1072.46      89 1063.29   158.2 1039.56   217.5 1021.11
   237.3 1012.54   247.2    1010   257.1 1013.25     267 1014.75   296.6 1015.92
   306.5 1015.12   326.3 1009.42   336.2 1007.41     356 1005.98   385.6 1006.06
   393.51004.865   405.4 1004.06   408.71005.009   415.3 1006.92     445  1025.5
   454.8  1027.4   474.6 1027.46   484.5 1034.53   494.4 1044.57   504.3  1050.7
   524.1 1059.09   553.7 1068.09   593.3 1083.03   672.4 1105.18   711.9 1118.18
#Mann= 3 , 0 , 0
       0     .08       0   393.5    .045       0   408.7     .08       0
#XS Ineff= 2 , 0
           296.9 1015.77
Permanent Ineff=
       F       F
Bank Sta=393.5,408.7
XS Rating Curve= 0 ,0
Exp/Cntr=0.3,0.1

Type RM Length L Ch R = 1 ,20597.3 ,354.7,351.7,348.6
XS GIS Cut Line= 2
      1752106.79      431211.519     1752734.035      431076.091
#Sta/Elev= 30
       0 1086.81    19.7 1079.53    39.5 1073.44   118.5 1052.18   197.4 1028.45
   207.3 1024.55   217.2 1018.92   227.1 1011.91   236.9 1010.89   246.8 1011.71
   256.7 1011.48   266.6 1012.44   276.4    1011   296.2 1005.81     3181004.202
   325.8 1002.94   335.7 1002.97   355.4 1007.75   414.6 1012.44   424.5  1013.6
   444.2 1017.99   454.1  1018.3     464 1020.46   483.7 1034.14   503.5    1043
   523.2 1050.89     543 1058.03   602.2 1074.53     622  1079.5   641.7 1086.24
#Mann= 3 , 0 , 0
       0     .08       0     318    .045       0   335.7     .08       0
Bank Sta=318,335.7
XS Rating Curve= 0 ,0
Exp/Cntr=0.3,0.1

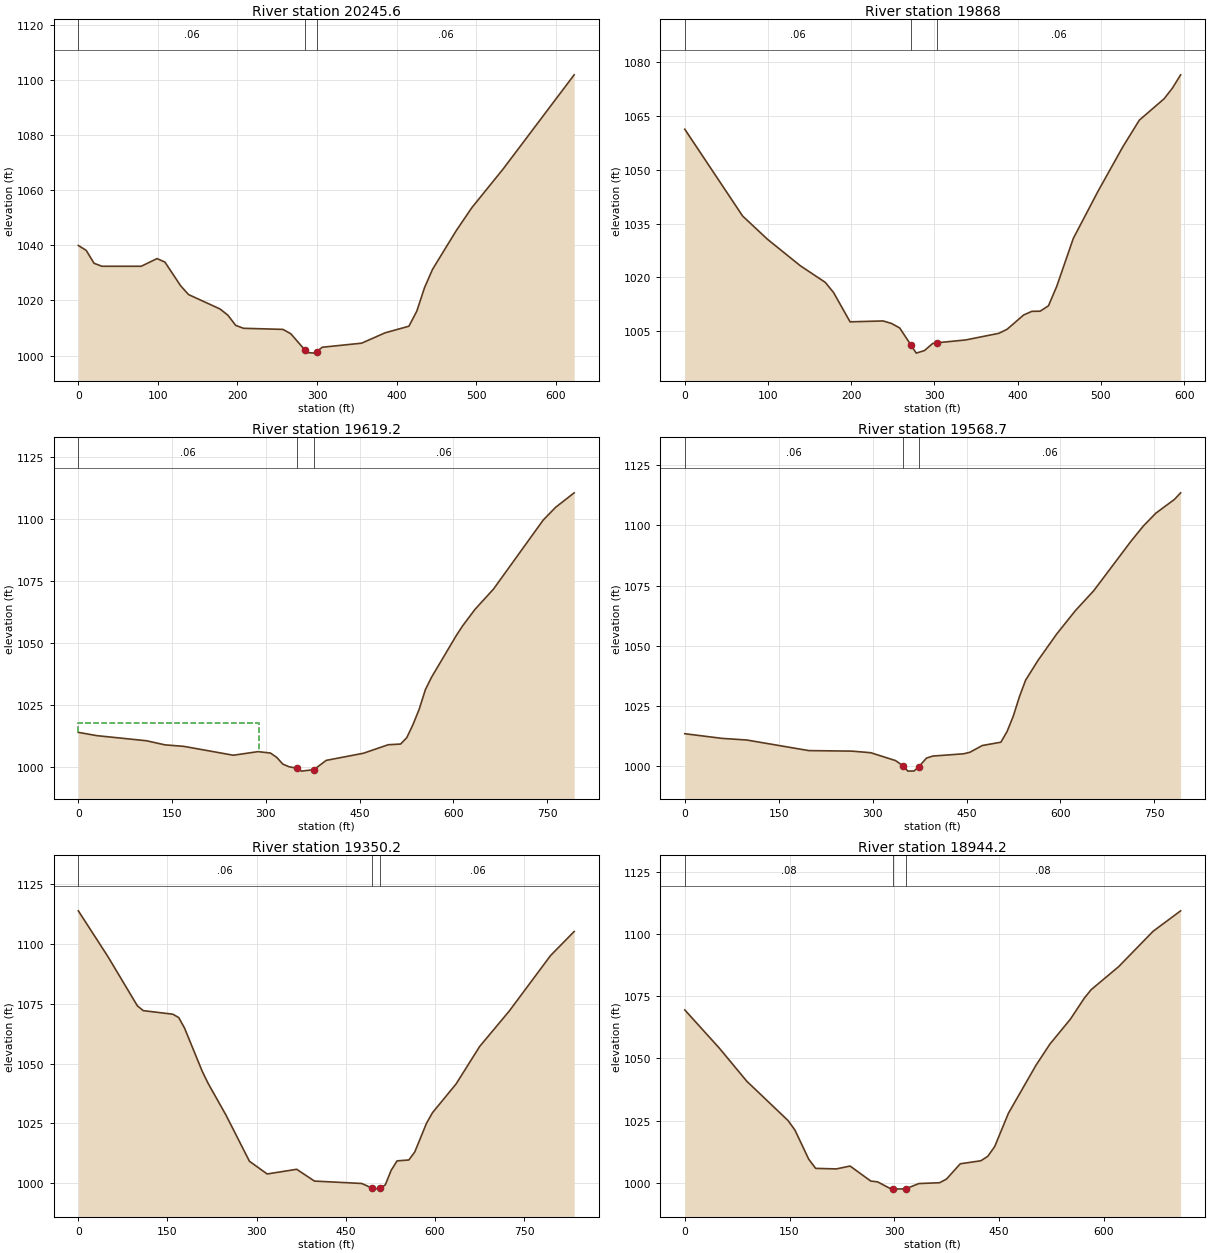
Type RM Length L Ch R = 1 ,20245.6 ,377.5,377.7,377.5
XS GIS Cut Line= 2
     1752199.499       431586.99     1752785.294      431374.326
#Sta/Elev= 30
       0 1039.93     9.9 1038.15    19.8 1033.47    29.7 1032.39    79.1 1032.39
    98.9 1035.17   108.8 1033.92   128.6 1025.31   138.5 1022.13   178.1 1016.89
     188 1014.65   197.8 1010.94   207.7 1009.89   257.2 1009.49   267.1  1007.9
   284.31002.171   286.9  1001.1   296.8 1000.88   299.4 1001.44   306.7 1003.02
   356.1 1004.49   385.8 1008.27   415.5 1010.64   425.4  1016.1   435.2 1024.68
   445.2 1031.28   474.8 1045.22   494.6 1053.64   534.2 1067.78   623.2 1101.83
#Mann= 3 , 0 , 0
       0     .06       0   284.3    .045       0   299.4     .06       0
Bank Sta=284.3,299.4
XS Rating Curve= 0 ,0
Exp/Cntr=0.3,0.1

Type RM Length L Ch R = 1 ,19868   ,259,248.8,238.5
XS GIS Cut Line= 2
     1752289.369      431950.962     1752849.456      431747.632
#Sta/Elev= 30
       0 1061.36    69.5 1037.14    99.3 1030.67     139 1023.24   168.8 1018.64
   178.8 1015.79   198.6 1007.62   238.3 1007.87   248.3 1007.18   258.2 1005.92
   271.6 1001.21   278.1  998.89     288  999.61   297.9 1001.59   303.51001.786
   337.6 1002.57   377.4 1004.42   387.3 1005.55   407.2 1009.54   417.1 1010.55
     427 1010.59     437  1012.1   446.9  1017.5   466.8 1030.87   496.5 1044.04
   526.3 1056.43   546.2  1063.9     576 1069.87   585.9 1072.82   595.8 1076.54
#Mann= 3 , 0 , 0
       0     .06       0   271.6    .045       0   303.5     .06       0
Bank Sta=271.6,303.5
XS Rating Curve= 0 ,0
Exp/Cntr=0.3,0.1

Type RM Length L Ch R = 1 ,19619.2 ,50.4,50.6,50.7
XS GIS Cut Line= 2
     1752429.085      432324.075     1752981.254      431754.305
#Sta/Elev= 30
       0    1014    29.8 1012.67   109.1 1010.62   138.8 1008.96   168.6 1008.37
     248 1004.79   287.6 1006.24   307.4 1005.67   317.4 1003.94   327.3  1001.2
   337.2 1000.16   349.3999.5756     357  998.39   376.9  998.98   396.7 1002.72
   456.2 1005.59   495.9 1009.02   515.7 1009.29   525.6 1011.89   535.6 1017.18
   545.5 1023.36   555.4 1031.24   565.3 1036.24     605 1053.07   614.9 1056.87
   634.7 1063.51   664.5 1071.74   743.8 1099.45   763.7  1104.6   793.4 1110.44
#Mann= 3 , 0 , 0
       0     .06       0   349.3    .045       0   376.9     .06       0
#XS Ineff= 2 , 0
          289.81 1017.68
Permanent Ineff=
       F       F
Bank Sta=349.3,376.9
XS Rating Curve= 0 ,0
Exp/Cntr=0.3,0.1

Type RM Length L Ch R = 1 ,19568.7 ,223.8,218.4,212.8
XS GIS Cut Line= 2
     1752465.243      432354.312     1753021.382      431790.605
#Sta/Elev= 30
       0 1013.57    59.4 1011.64      99 1010.96     198 1006.57   267.3 1006.35
     297 1005.69   336.5 1002.44   348.7 1000.23   356.3  998.06   366.2  998.13
   373.7 999.872     386 1003.46   395.9  1004.3   445.4 1005.25   455.3 1005.87
   475.1 1008.68   504.8 1010.05   514.7 1014.48   524.6 1020.83   534.5 1028.96
   544.4 1035.81   564.2    1044   593.9 1054.88   623.6 1064.53   653.3 1072.92
   712.7  1093.4   732.5 1099.72   752.3    1105     782 1110.71   791.9 1113.44
#Mann= 3 , 0 , 0
       0     .06       0   348.7    .045       0   373.7     .06       0
Bank Sta=348.7,373.7
XS Rating Curve= 0 ,0
Exp/Cntr=0.3,0.1

Type RM Length L Ch R = 1 ,19350.2 ,414.2,406,399.5
XS GIS Cut Line= 2
     1752652.663      432617.339     1753080.847      431901.227
#Sta/Elev= 30
       0 1113.91    49.7 1094.82    99.3 1074.21   109.3 1072.17   158.9 1070.69
   168.9 1069.29   178.8 1064.84   208.6 1046.76   218.5 1041.72   248.3 1028.57
     288 1009.18   317.8 1003.87   367.5 1005.83   397.3  1000.9   476.8   999.9
   493.5  998.06   496.6  997.53   508.5     998   516.5  999.29   526.4 1005.37
   536.4 1009.35   556.2 1009.72   566.2 1013.09     586 1025.12     596  1029.5
   635.7 1041.51   675.4 1057.19   725.1 1071.98   794.6 1095.18   834.4 1105.26
#Mann= 3 , 0 , 0
       0     .06       0   493.5    .045       0   508.5     .06       0
#XS Ineff= 2 , 0
           366.7 1005.71
Permanent Ineff=
       F       F
Bank Sta=493.5,508.5
XS Rating Curve= 0 ,0
Exp/Cntr=0.3,0.1

Type RM Length L Ch R = 1 ,18944.2 ,462.5,458,450.8
XS GIS Cut Line= 2
     1753167.192      432698.937     1753359.309      432015.351
#Sta/Elev= 30
       0 1069.51    49.3 1054.21    88.8 1040.86   147.9 1025.06   157.8  1021.2
   177.5 1009.53   187.4 1005.85     217 1005.63   236.7 1006.79   266.3 1000.76
   276.1 1000.43   295.9  997.51   298.7  997.51   316.4 997.639   335.3  999.75
   364.9 1000.08   374.8 1001.55   394.5 1007.69   424.1 1008.91   433.9  1010.7
   443.8 1014.59   463.5 1028.01     503  1047.3   522.7 1055.72   552.3 1065.83
     572 1074.18   581.9 1077.63   621.3 1086.89   670.6 1101.09   710.1 1109.33
#Mann= 3 , 0 , 0
       0     .08       0   298.7    .045       0   316.4     .08       0
Bank Sta=298.7,316.4
XS Rating Curve= 0 ,0
Exp/Cntr=0.3,0.1

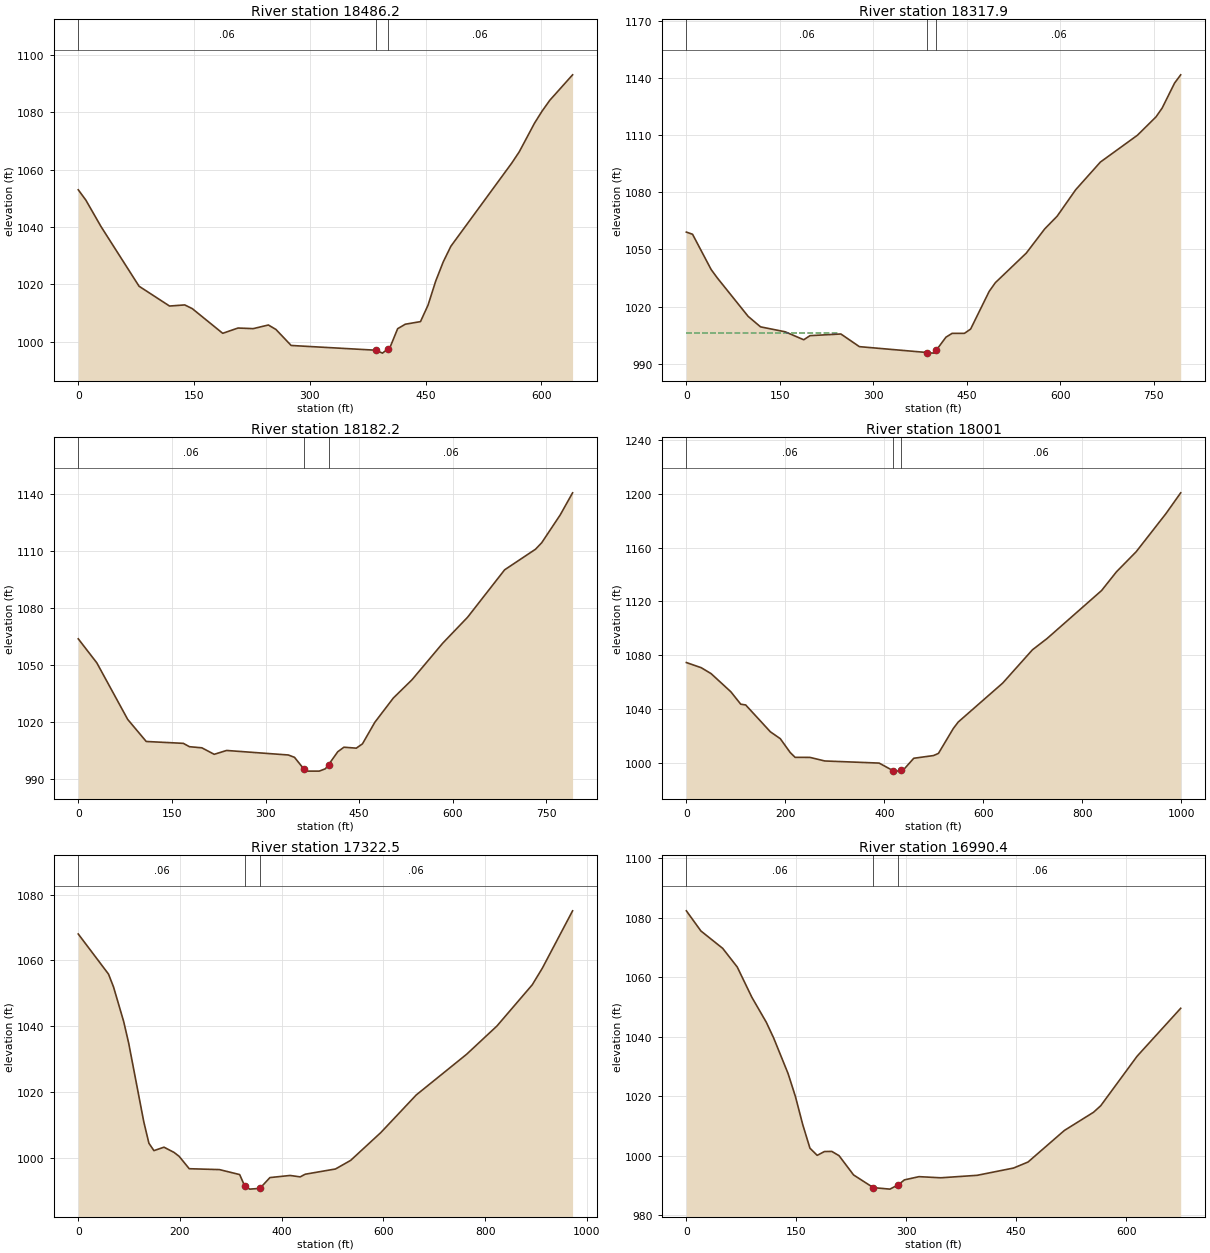
Type RM Length L Ch R = 1 ,18486.2 ,164.9,168.3,171.8
XS GIS Cut Line= 2
     1753672.178      432775.969     1753655.889      432135.618
#Sta/Elev= 30
       0 1052.97     9.8 1049.39    29.6  1040.1    78.8 1019.34   118.3 1012.43
     138 1012.82   147.8 1011.52   187.2 1002.92     207 1004.76   226.7 1004.55
   246.4 1005.82   256.2 1004.26   275.9  998.68   385.7 997.022   394.2  996.01
   400.8  997.36     404  998.01   413.9 1004.53   423.8 1006.09   443.5    1007
   453.3 1012.76   463.2 1021.12     473 1027.84   482.9 1033.29   561.7 1062.26
   571.6 1066.26   591.3 1076.22   601.1 1080.41     611 1084.16   640.6 1093.06
#Mann= 3 , 0 , 0
       0     .06       0   385.7    .045       0   400.8     .06       0
#XS Ineff= 2 , 0
          246.15 1005.71
Permanent Ineff=
       F       F
Bank Sta=385.7,400.8
XS Rating Curve= 0 ,0
Exp/Cntr=0.3,0.1

Type RM Length L Ch R = 1 ,18317.9 ,135.5,135.7,135.9
XS GIS Cut Line= 2
     1753779.111      432792.636     1753879.748      432005.616
#Sta/Elev= 30
       0 1059.11     9.9 1057.99    39.7 1039.52    49.6  1035.1    99.2 1014.89
     119 1009.41   158.7  1006.8   188.4 1002.63   198.4 1004.79     248 1005.66
   277.7  999.02   386.4  995.94   396.7  995.62   401.4  997.28   416.6 1003.98
   426.5 1005.99   446.3    1006   456.2 1008.23     486    1028   495.9 1032.57
   545.5 1048.08   575.2 1060.81   595.1 1067.46   624.8 1081.32   664.5 1095.86
     724 1109.95   753.8 1119.58   763.7 1124.24   783.5 1137.26   793.4 1141.63
#Mann= 3 , 0 , 0
       0     .06       0   386.4    .045       0   401.4     .06       0
#XS Ineff= 2 , 0
          244.46 1006.17
Permanent Ineff=
       F       F
Bank Sta=386.4,401.4
XS Rating Curve= 0 ,0
Exp/Cntr=0.3,0.1

Type RM Length L Ch R = 1 ,18182.2 ,183.2,181.1,179.1
XS GIS Cut Line= 2
     1753911.358      432800.941     1754018.807      432016.396
#Sta/Elev= 30
       0 1063.68    29.7 1051.07    79.2 1021.33   108.9 1009.73   168.3 1008.75
   178.2 1006.98     198  1006.4   217.8 1002.99   237.6 1005.01   336.5 1002.63
   346.4 1001.41   361.6995.2001   366.2  994.15     386  994.15   395.9  995.39
   400.9997.4759   415.7 1004.33   425.6 1006.72   445.4 1006.22   455.3 1008.49
   475.1 1019.81   504.8 1032.59   534.5 1042.11     584 1061.43   623.6 1074.98
     683 1099.93   732.5 1110.76   742.4 1114.15   772.1  1128.8   791.9  1140.4
#Mann= 3 , 0 , 0
       0     .06       0   361.6    .045       0   400.9     .06       0
Bank Sta=361.6,400.9
XS Rating Curve= 0 ,0
Exp/Cntr=0.3,0.1

Type RM Length L Ch R = 1 ,18001   ,650.2,678.6,706.8
XS GIS Cut Line= 2
     1754123.276      432861.197     1754168.266      431863.152
#Sta/Elev= 30
       0 1074.61      30 1070.78      50 1066.37    89.9 1052.88   109.9 1043.64
   119.9 1043.08   169.8 1023.11   189.8 1018.01   209.8 1007.76   219.8 1004.12
   249.8 1004.09   279.7 1001.44   389.6  999.86   418.5994.0734   429.6  993.88
   433.7994.4232   439.6   995.2   459.6 1003.44   499.5 1005.45   509.5 1007.07
   539.5 1025.56   549.5  1030.4   639.4 1059.36   699.3 1084.03   729.3 1092.56
   839.2 1128.14   869.2 1142.04   909.1 1156.99   969.1 1185.25   999.1 1200.79
#Mann= 3 , 0 , 0
       0     .06       0   418.5    .045       0   433.7     .06       0
Bank Sta=418.5,433.7
XS Rating Curve= 0 ,0
Exp/Cntr=0.3,0.1

Type RM Length L Ch R = 1 ,17322.5 ,326.4,332,337.5
XS GIS Cut Line= 2
     1754210.545      432845.374     1755144.315      432575.356
#Sta/Elev= 30
       0    1068    59.5 1055.82    69.4 1051.89    89.3 1041.42    99.2 1034.81
   128.9 1010.91   138.9 1004.44   148.8 1002.19   168.6 1003.23   188.4 1001.64
   198.4 1000.45   218.2  996.69   277.7  996.42   317.4  994.91   327.3  991.44
   337.2  990.49   357.1  990.71   376.9     994   416.6  994.64   436.4  994.21
   446.3  995.02   505.8  996.61   535.6  999.22   595.1  1007.7   664.6  1019.1
   763.7 1031.47   823.2 1040.04   892.7 1052.57   912.5 1057.61     972 1075.04
#Mann= 3 , 0 , 0
       0     .06       0   327.3    .045       0   357.1     .06       0
Bank Sta=327.3,357.1
XS Rating Curve= 0 ,0
Exp/Cntr=0.3,0.1

Type RM Length L Ch R = 1 ,16990.4 ,436.9,445.1,452.2
XS GIS Cut Line= 2
     1754303.821      433083.241     1754977.825      433059.691
#Sta/Elev= 30
       0 1082.25    19.8 1075.49    49.6 1069.63    69.4 1063.38    89.3 1053.23
   109.1 1044.79     119 1039.58   138.8 1027.55   148.8 1019.85   158.7 1010.48
   168.6  1002.5   178.5  1000.1   188.4 1001.38   198.4 1001.42   208.3  999.99
   228.1  993.52     255 989.252   277.7  988.75     289 990.194   297.5  991.86
   317.4  992.94   347.1  992.56   396.7  993.39   446.3  995.83   466.1  997.85
   515.7 1008.46   555.4 1014.56   565.3 1016.77   614.9  1033.4   674.4 1049.51
#Mann= 3 , 0 , 0
       0     .06       0     255    .045       0     289     .06       0
Bank Sta=255,289
XS Rating Curve= 0 ,0
Exp/Cntr=0.3,0.1

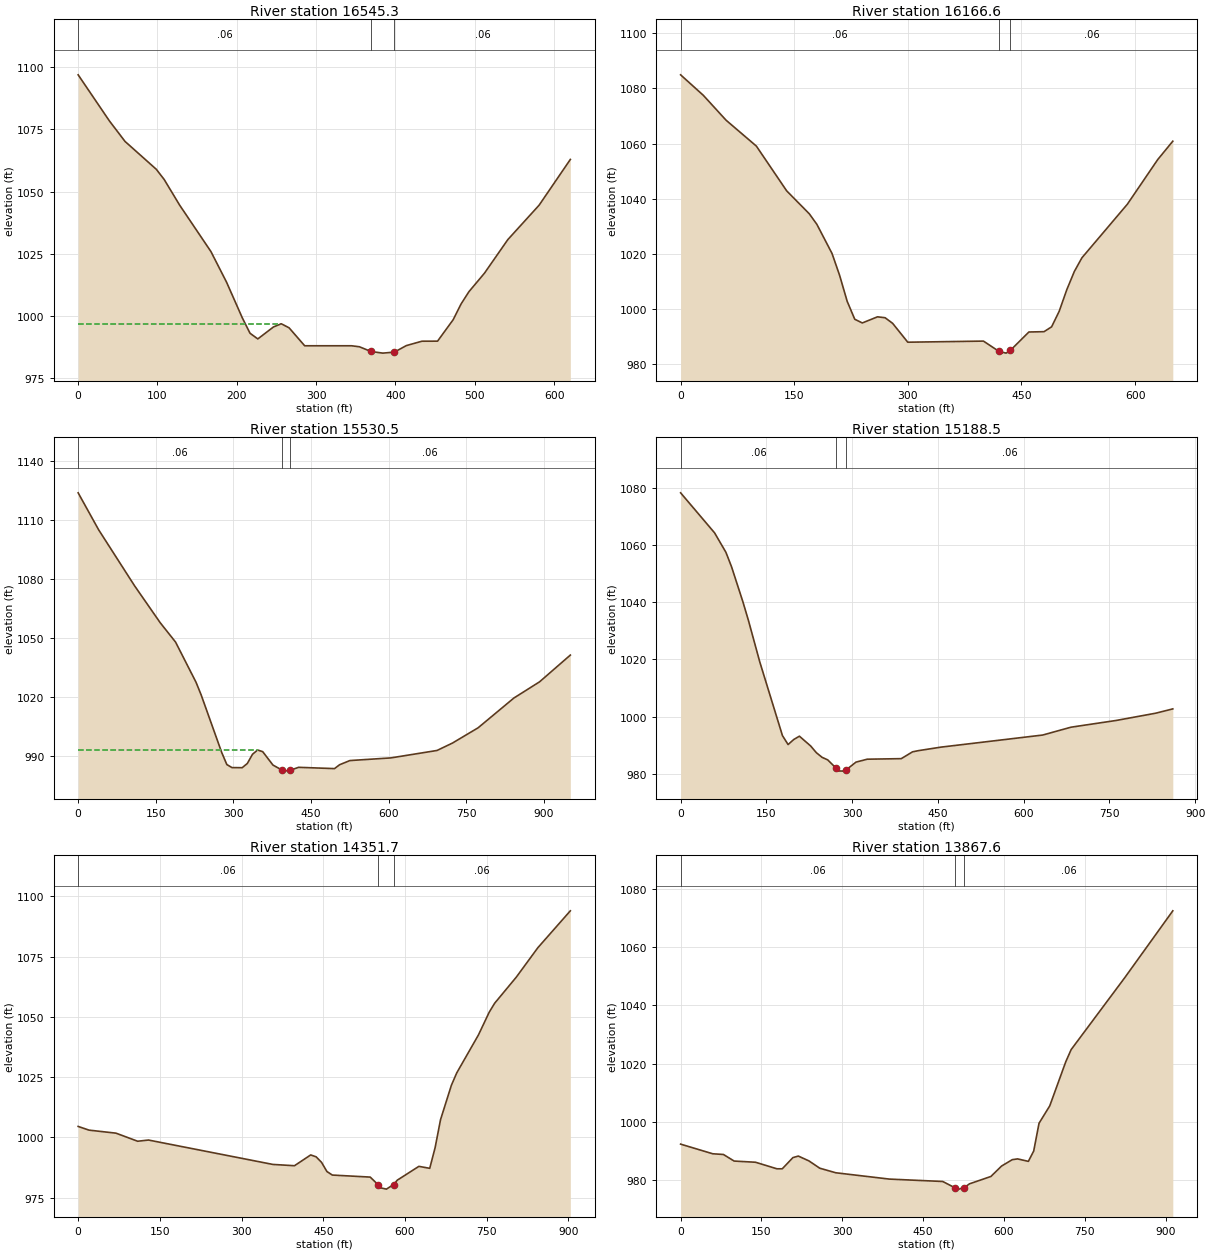
Type RM Length L Ch R = 1 ,16545.3 ,378.6,378.7,378.6
XS GIS Cut Line= 2
     1754215.697      433380.662     1754805.653      433573.044
#Sta/Elev= 30
       0    1097    39.4 1078.44    59.1 1070.18    98.5 1058.96   108.4 1054.88
     128  1044.5   167.4 1025.82   187.1 1013.49   206.8  999.23   216.7  992.92
   226.5  990.64   246.2  995.45   256.1  996.74   265.9  995.12   285.6  987.88
   344.7  987.88   354.6  987.48   369.2 985.582   384.1  984.92   398.7 985.327
   413.7  987.95   433.4  989.72   453.1  989.74   472.8  998.38   482.6 1004.63
   492.5  1009.6   512.2  1017.1   541.7 1030.64   581.1 1044.49   620.5 1062.92
#Mann= 3 , 0 , 0
       0     .06       0   369.2    .045       0   398.7     .06       0
#XS Ineff= 2 , 0
          255.45  996.68
Permanent Ineff=
       F       F
Bank Sta=369.2,398.7
XS Rating Curve= 0 ,0
Exp/Cntr=0.3,0.1

Type RM Length L Ch R = 1 ,16166.6 ,651.9,636.1,619.1
XS GIS Cut Line= 2
     1754073.672       433727.74     1754691.419      433929.184
#Sta/Elev= 30
       0 1084.94      30  1077.5      60 1068.49     100  1059.1     140 1042.88
   169.9 1034.55   179.9 1030.73   199.9 1020.17   209.9 1012.25   219.9 1002.83
   229.9  996.32   239.9  994.98   259.9   997.2   269.9  996.88   279.9  994.84
   299.9     988   399.8   988.4   420.4984.6572   429.8  984.04   435.5  985.08
   459.8   991.7   479.8  991.82   489.8  993.58   499.8  999.21   509.8 1007.01
   519.8 1013.64   529.8  1018.6   589.8 1038.03   629.8 1054.18   649.8 1060.88
#Mann= 3 , 0 , 0
       0     .06       0   420.4    .045       0   435.5     .06       0
Bank Sta=420.4,435.5
XS Rating Curve= 0 ,0
Exp/Cntr=0.3,0.1

Type RM Length L Ch R = 1 ,15530.5 ,340.1,342,344.4
XS GIS Cut Line= 2
     1754008.969      434560.813     1754887.732      434197.346
#Sta/Elev= 30
       0 1124.01    39.6 1105.18     109 1076.67   158.5 1057.88   188.2 1048.01
   227.8 1027.52   237.7 1021.08   277.4  991.76   287.3  985.63   297.2  984.08
     317  984.03   326.9  986.19   336.8  990.83   346.7  993.05   356.6  992.19
   376.4  985.37   393.9  982.81   406.1  982.28   408.9  982.66     426  984.22
   495.3  983.56   505.2  985.54     525  987.66   604.3  989.02   693.4   992.8
   723.1  996.55   772.7 1004.33     842 1019.52   891.5 1027.75     951 1041.38
#Mann= 3 , 0 , 0
       0     .06       0   393.9    .045       0   408.9     .06       0
#XS Ineff= 2 , 0
           348.1  993.06
Permanent Ineff=
       F       F
Bank Sta=393.9,408.9
XS Rating Curve= 0 ,0
Exp/Cntr=0.3,0.1

Type RM Length L Ch R = 1 ,15188.5 ,819.4,836.8,852.3
XS GIS Cut Line= 2
     1754271.744      434800.738     1755085.327      434519.287
#Sta/Elev= 30
       0 1078.37    59.4 1064.35    79.2 1057.55    89.1 1052.46   108.8 1040.29
   118.7 1033.62   138.5 1019.11   178.1  993.33     188  990.19   197.9  991.96
   207.8  993.12   227.6  989.66   237.5  987.32   247.4  985.72   257.3  984.82
   272.1981.8881   277.1  980.94     287  980.88   289.1981.2462   306.8  984.04
   326.5  985.06   385.9  985.25   405.7  987.64   415.6  988.04   455.2  989.28
   633.3  993.52   682.8  996.27   761.9  998.63   831.2 1001.18   860.9 1002.68
#Mann= 3 , 0 , 0
       0     .06       0   272.1    .045       0   289.1     .06       0
Bank Sta=272.1,289.1
XS Rating Curve= 0 ,0
Exp/Cntr=0.3,0.1

Type RM Length L Ch R = 1 ,14351.7 ,495.7,484.1,461.6
XS GIS Cut Line= 2
     1754000.717      435136.598     1754819.301       435519.01
#Sta/Elev= 30
       0 1004.58    19.9 1003.05    69.5 1001.79   109.2  998.44   129.1  998.94
   357.4  988.83   397.1  988.29   426.9  992.77   436.9  991.97   446.8  989.69
   456.7  985.88   466.6  984.42   536.1  983.58   550.3 980.502     556  979.08
   565.9  978.59     579 980.487   585.8   982.3   625.5  988.03   645.4  987.21
   655.3  995.81   665.2 1007.37   685.1 1021.62     695 1026.79   734.7 1042.46
   754.6 1051.94   764.5 1055.63   804.2 1066.44   843.9 1078.68   903.5 1093.96
#Mann= 3 , 0 , 0
       0     .06       0   550.3    .045       0     579     .06       0
Bank Sta=550.3,579
XS Rating Curve= 0 ,0
Exp/Cntr=0.3,0.1

Type RM Length L Ch R = 1 ,13867.6 ,69.9,70.1,69
XS GIS Cut Line= 2
     1753864.093      435841.721     1754762.861      435680.265
#Sta/Elev= 30
       0  992.37    59.6  989.06    79.4  988.82    99.3  986.56     139  986.15
   178.7   983.9   188.6   983.9   208.4  987.75   218.4  988.27   238.2   986.6
   258.1  984.11   287.8  982.54   387.1  980.37   486.4  979.54   509.9 977.293
   516.1  976.92   526.3977.4662     536  978.74   575.7  981.27   595.5  984.85
   615.4  987.04   625.3   987.3   645.2  986.45   655.1     990     665  999.54
   684.9 1005.52   714.6 1020.66   724.6 1024.84   823.8 1049.47   913.2 1072.49
#Mann= 3 , 0 , 0
       0     .06       0   509.9    .045       0   526.3     .06       0
#XS Ineff= 2 , 0
          219.66  988.16
Permanent Ineff=
       F       F
Bank Sta=509.9,526.3
XS Rating Curve= 0 ,0
Exp/Cntr=0.3,0.1

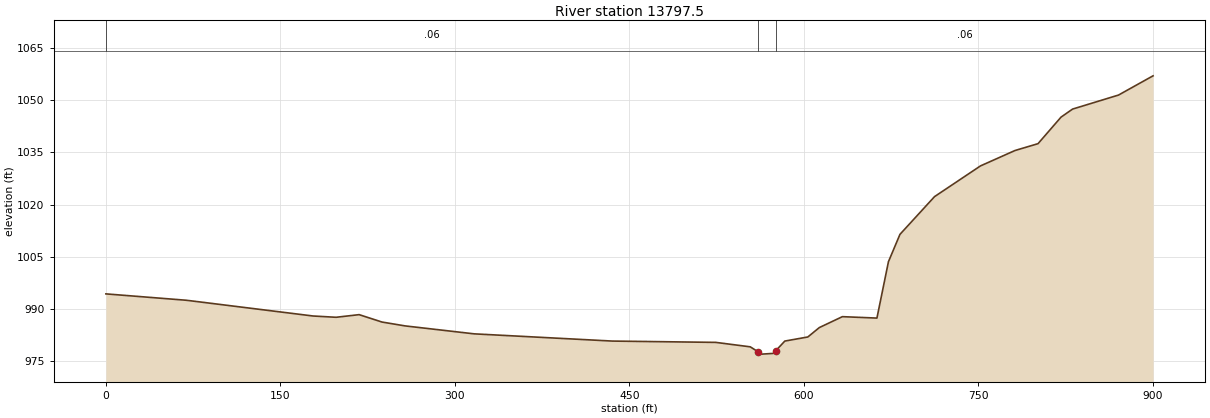
Type RM Length L Ch R = 1 ,13797.5 ,319.5,318.6,317
XS GIS Cut Line= 2
     1753852.984      435907.267     1754739.126       435748.08
#Sta/Elev= 30
       0  994.27    69.3  992.43   178.1   987.9   197.9  987.53   217.7  988.29
   237.4  986.16   257.2  985.05   316.6  982.76   435.3  980.68   524.4   980.3
     554  979.02   560.8  977.58   563.9  976.92   573.8  977.13   575.8  977.85
   583.7  980.68   603.5  981.86   613.4  984.57   633.2  987.71   662.9   987.3
   672.8 1003.53   682.7 1011.41   712.4 1022.27   751.9 1031.12   781.6 1035.56
   801.4 1037.53   821.2 1045.18   831.1 1047.49   870.6 1051.53   900.3 1057.07
#Mann= 3 , 0 , 0
       0     .06       0   560.8    .045       0   575.8     .06       0
Bank Sta=560.8,575.8
XS Rating Curve= 0 ,0
Exp/Cntr=0.3,0.1