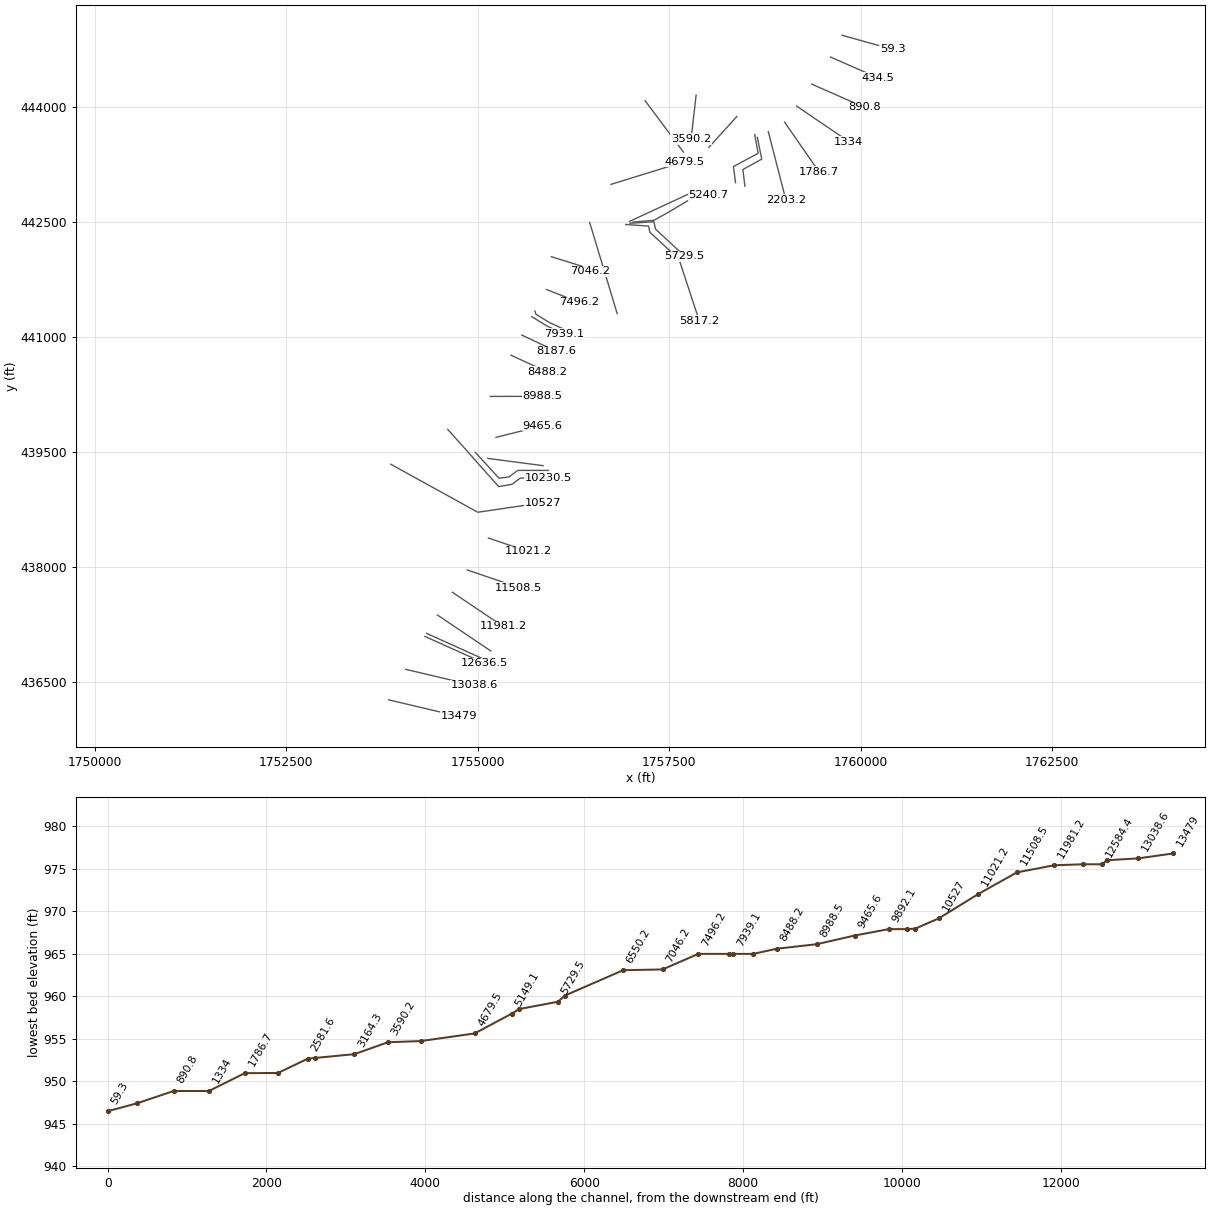
HEC-RAS study MiraclerRn.prj: MiraclerRn

--- MiraclerRn.g01 (geometry) --- (continued)

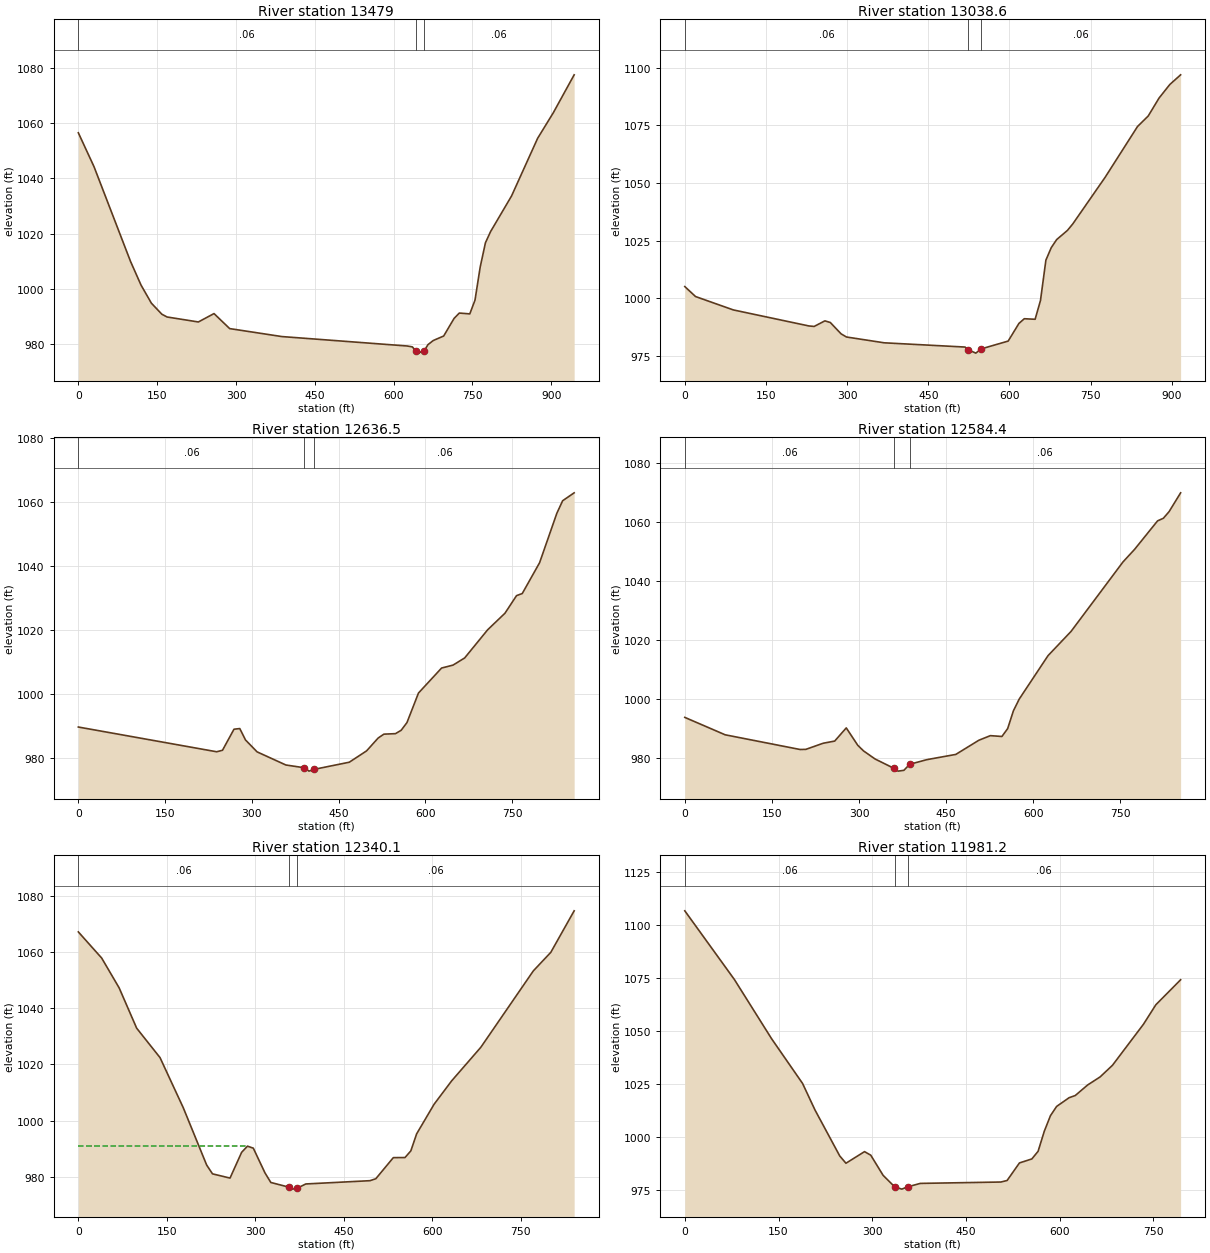
Type RM Length L Ch R = 1 ,13479   ,439.2,440.3,439.2
XS GIS Cut Line= 2
     1753837.408      436262.848      1754755.58      436045.646
#Sta/Elev= 30
       0  1056.5    29.8 1044.26    99.3 1009.99   119.2 1001.46     139  994.88
   158.9  990.89   168.8  989.88   228.4  988.08   258.2  991.11     288  985.68
   387.3   982.8   625.7  979.39   635.6  979.07   642.7  977.47   645.6  976.81
   657.8977.5508   665.4  979.89   675.4  981.37   695.2     983   715.1  989.39
     725   991.3   744.9     991   754.8  995.96   764.7 1007.94   774.7 1016.74
   784.6 1020.81   824.3 1033.62     874  1054.5   903.8 1063.74   943.5 1077.46
#Mann= 3 , 0 , 0
       0     .06       0   642.7    .045       0   657.8     .06       0
Bank Sta=642.7,657.8
XS Rating Curve= 0 ,0
Exp/Cntr=0.3,0.1

Type RM Length L Ch R = 1 ,13038.6 ,407.9,402.2,396.6
XS GIS Cut Line= 2
     1754060.924      436661.062     1754952.571      436450.135
#Sta/Elev= 30
       0 1005.07    19.9 1000.75    89.6  994.96   229.1  988.02     239  987.79
   258.9  990.21   268.9  989.51   288.8  984.59   298.8  983.22   368.5   980.7
   517.9  978.86   523.9  977.68   537.8  976.23   547.8  978.07   597.6  981.45
   617.5   989.1   627.4  991.14   647.4   990.9   657.3  999.02   667.3 1016.51
   677.2 1021.93   687.2 1025.44   707.1 1029.41   717.1 1032.26   776.8 1052.44
   836.6 1074.43   856.5 1079.03   876.4 1086.77   896.3 1092.65   916.3 1096.85
#Mann= 3 , 0 , 0
       0     .06       0   523.9    .045       0   547.8     .06       0
Bank Sta=523.9,547.8
XS Rating Curve= 0 ,0
Exp/Cntr=0.3,0.1

Type RM Length L Ch R = 1 ,12636.5 ,52.8,52.1,52.7
XS GIS Cut Line= 2
     1754311.699      437090.962     1755092.985      436738.451
#Sta/Elev= 30
       0  989.76   239.2  982.04   249.2  982.51   269.1  989.08   279.1  989.28
     289  985.72     309  982.01   358.8  977.91   390.9977.0467   398.7     976
   408.2 976.575   468.4  978.78   498.3  982.32   518.3  986.33   528.2  987.54
   548.2  987.69   558.1  988.75   568.1  991.16     588 1000.37   627.9 1008.16
   647.8 1009.09   667.8 1011.31   707.6 1020.11   737.5 1025.27   757.5 1030.76
   767.4 1031.42   797.3 1041.01   827.2 1056.47   837.2 1060.37   857.1 1062.84
#Mann= 3 , 0 , 0
       0     .06       0   390.9    .045       0   408.2     .06       0
#XS Ineff= 2 , 0
          277.24  989.23
Permanent Ineff=
       F       F
Bank Sta=390.9,408.2
XS Rating Curve= 0 ,0
Exp/Cntr=0.3,0.1

Type RM Length L Ch R = 1 ,12584.4 ,245.8,244.3,240.6
XS GIS Cut Line= 2
     1754334.527      437130.095     1755112.723      436778.979
#Sta/Elev= 30
       0  993.77    69.5  987.86   198.5  982.87   208.5  982.92   238.2  984.99
   258.1  985.73     278   990.2   297.8  984.31   307.7   982.4   327.6  979.65
     360976.4879   367.3  975.53   377.2   975.8   387.2  977.85   416.9  979.43
   466.6   981.2   506.3  986.01   526.1  987.57     546  987.29   555.9  989.96
   565.8     996   575.8  999.98   625.4 1014.72   665.1 1022.96   754.5 1046.53
   774.3 1050.76     814 1060.46     824 1061.35   833.9 1063.61   853.7 1069.98
#Mann= 3 , 0 , 0
       0     .06       0     360    .045       0   387.2     .06       0
#XS Ineff= 2 , 0
          278.12  989.85
Permanent Ineff=
       F       F
Bank Sta=360,387.2
XS Rating Curve= 0 ,0
Exp/Cntr=0.3,0.1

Type RM Length L Ch R = 1 ,12340.1 ,358.8,358.9,358.7
XS GIS Cut Line= 2
     1754474.694      437370.382     1755172.135      436900.972
#Sta/Elev= 30
       0 1067.28    39.6 1057.95    69.2 1047.32    98.9 1032.94   138.5 1022.45
     178 1004.53   217.6  984.12   227.5  980.98   257.2  979.47   276.9  988.66
   286.8  990.86   296.7  990.14   316.5  981.31   326.4   977.9   356.5 976.268
     366  975.53   371.6  975.92   385.7  977.37   494.5  978.54   504.4  979.24
   534.1  986.76   553.9   986.8   563.8  989.18   573.6  995.24   603.3 1005.83
     633 1014.15   682.4 1026.11   771.5 1053.38   801.1 1059.99   840.7  1074.8
#Mann= 3 , 0 , 0
       0     .06       0   356.5    .045       0   371.6     .06       0
#XS Ineff= 2 , 0
          286.98  991.07
Permanent Ineff=
       F       F
Bank Sta=356.5,371.6
XS Rating Curve= 0 ,0
Exp/Cntr=0.3,0.1

Type RM Length L Ch R = 1 ,11981.2 ,465.9,472.7,478.8
XS GIS Cut Line= 2
     1754671.045      437666.804     1755329.331      437223.747
#Sta/Elev= 30
       0  1106.7    79.4 1074.29   138.9 1046.37   188.5 1025.26   208.3 1012.79
     248  991.06   257.9  987.63   287.6   993.1   297.6  991.44   317.4  981.92
   335.8  976.53   347.2  975.42   357.1  976.53   376.9  978.12   505.9  978.77
   515.8  979.49   535.6  987.78   555.4  989.66   565.4  993.26   575.3  1002.7
   585.2 1010.07   595.1 1014.44     615 1018.54   624.9 1019.58   644.7 1024.55
   664.6 1028.34   684.4 1033.83     734 1053.18   753.8 1062.37   793.5 1074.18
#Mann= 3 , 0 , 0
       0     .06       0   335.8    .045       0   357.1     .06       0
Bank Sta=335.8,357.1
XS Rating Curve= 0 ,0
Exp/Cntr=0.3,0.1

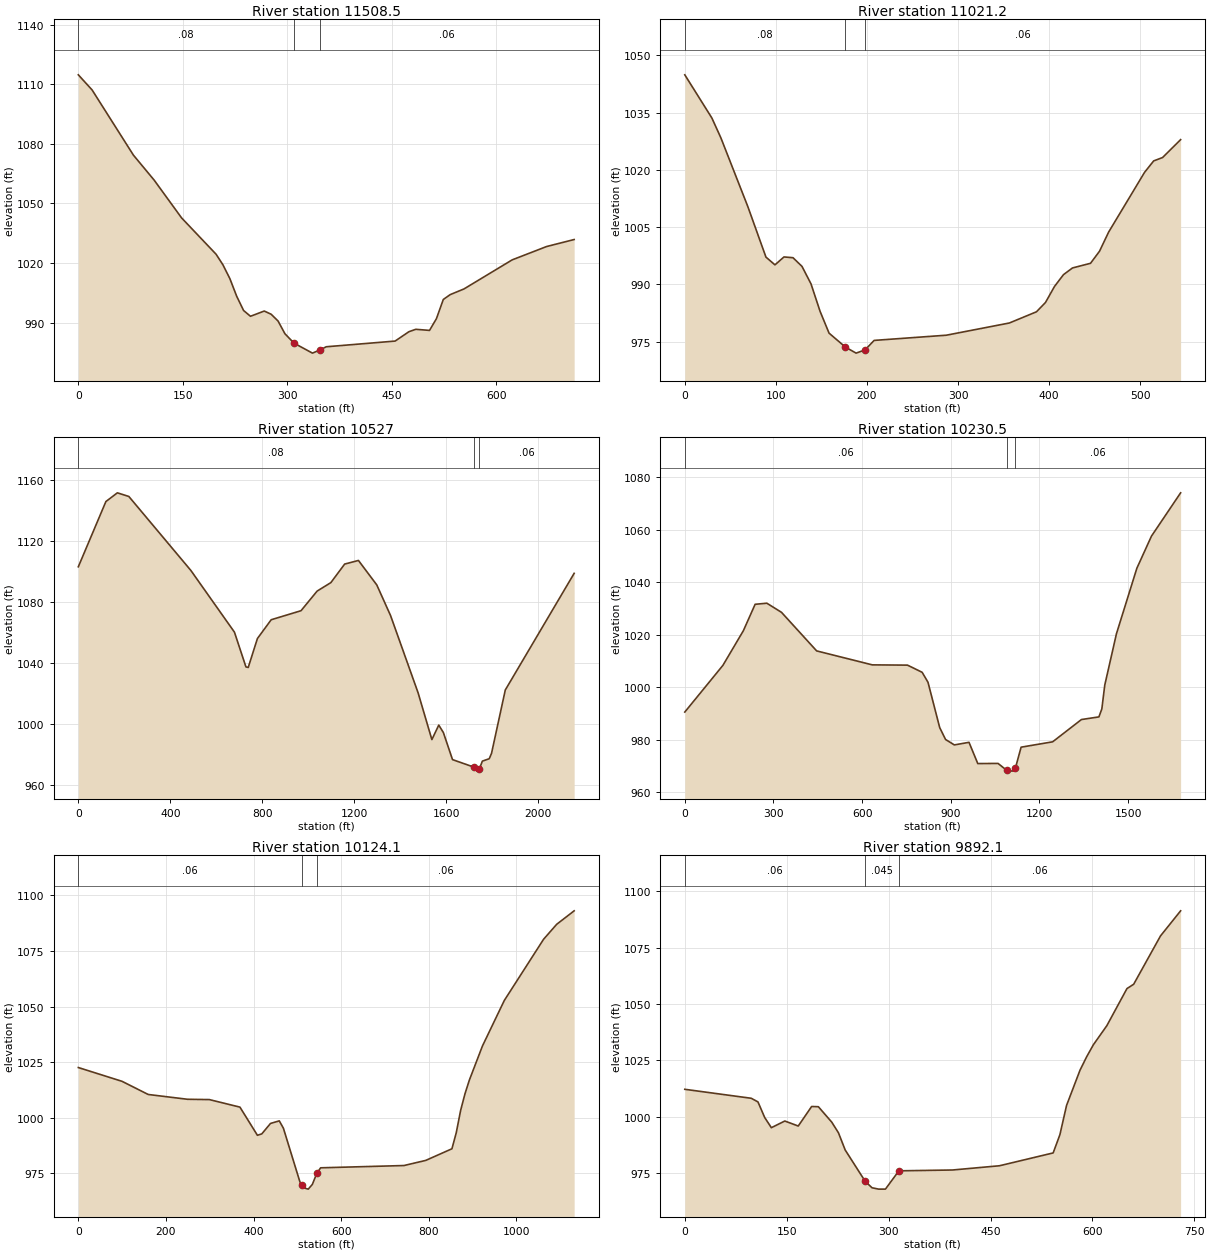
Type RM Length L Ch R = 1 ,11508.5 ,487.1,487.3,487.4
XS GIS Cut Line= 2
     1754864.416      437958.684     1755538.236       437728.67
#Sta/Elev= 30
       0 1114.71    19.8 1107.08    79.1 1074.28   108.8 1061.73   148.3 1042.66
   197.8 1024.38   207.7 1019.03   217.6  1012.1   227.4 1003.23   237.3  996.05
   247.2  993.14     267  995.77   276.9  994.16   286.8  990.75   296.7  984.33
   309.7 979.616   336.2  974.58   346.5976.1127     356  977.78   454.9  980.65
   474.7  985.36   484.6  986.58   504.3  986.02   514.2  991.91   524.1 1001.59
     534 1004.04   553.8  1006.9     623 1021.54   672.4 1028.25     712 1031.78
#Mann= 3 , 0 , 0
       0     .08       0   309.7    .045       0   346.5     .06       0
Bank Sta=309.7,346.5
XS Rating Curve= 0 ,0
Exp/Cntr=0.3,0.1

Type RM Length L Ch R = 1 ,11021.2 ,483.1,494.2,504.7
XS GIS Cut Line= 2
     1755140.816      438375.893      1755656.07      438200.006
#Sta/Elev= 30
       0 1044.89    29.7  1033.6    39.6  1028.4    69.3 1010.34    89.1  997.17
      99  995.14   108.9  997.21   118.8  997.01   128.7  994.73   138.6  990.15
   148.5  982.99   158.4  977.26   176.4   973.6   188.1  972.03     198  972.89
   207.9  975.36   287.1  976.72   356.4  979.92   386.1  982.85     396  985.28
   405.9  989.48   415.8  992.58   425.7  994.33   445.5  995.55   455.4  998.73
   465.3 1003.69   504.8 1019.36   514.8 1022.35   524.6 1023.24   544.4 1027.92
#Mann= 3 , 0 , 0
       0     .08       0   176.4    .045       0     198     .06       0
Bank Sta=176.4,198
XS Rating Curve= 0 ,0
Exp/Cntr=0.3,0.1

Type RM Length L Ch R = 1 ,10527   ,295.7,296.5,297
XS GIS Cut Line= 3
     1753865.751      439339.482     1755002.005      438712.262
     1755850.974      438837.035
#Sta/Elev= 30
       0 1103.05   119.8 1145.75   169.7 1151.48   219.6  1149.1   489.2 1100.66
   678.9  1060.2   728.8 1037.44   738.8 1037.09   778.7 1056.03   838.6 1068.34
   968.4 1074.27  1038.3  1087.1  1098.2 1092.68  1158.1 1104.81    1218 1107.18
  1297.9 1091.12  1357.7 1071.08  1477.5 1020.45  1537.3  989.84  1567.3  999.33
  1587.2  994.49  1627.1  976.72  1718.8971.8691  1736.9  969.18    1743970.3085
  1756.8  975.72  1786.8  977.31  1796.8  980.87  1856.6 1022.34    2156 1098.74
#Mann= 3 , 0 , 0
       0     .08       0  1718.8    .045       0    1743     .06       0
Bank Sta=1718.8,1743
XS Rating Curve= 0 ,0
Exp/Cntr=0.3,0.1

Type RM Length L Ch R = 1 ,10230.5 ,107.4,106.3,105.3
XS GIS Cut Line= 5
     1754609.638      439794.797     1755275.566      439046.828
     1755448.542      439077.317     1755556.943      439158.618
      1755922.22      439158.618
#Sta/Elev= 30
       0   990.5   128.9  1008.3   198.3 1021.55     238 1031.61   277.6 1032.03
   327.2 1028.55   446.2 1013.83   634.6  1008.5   753.6  1008.4   803.2 1005.67
     823 1001.86   862.6  984.57   882.5  980.03   912.2  977.96   961.8  978.95
   991.5  970.84    1060   970.9  1089.8968.2475  1108.8  967.96    1119969.1946
  1138.1   977.1  1244.8  979.14  1342.2  987.64  1401.4  988.65  1411.3   991.7
  1421.2 1000.78  1460.7 1020.36  1529.8 1045.36  1579.2 1057.61  1677.9 1074.14
#Mann= 3 , 0 , 0
       0     .06       0  1089.8    .045       0    1119     .06       0
Bank Sta=1089.8,1119
XS Rating Curve= 0 ,0
Exp/Cntr=0.3,0.1

Type RM Length L Ch R = 1 ,10124.1 ,237.3,232.1,226.5
XS GIS Cut Line= 5
     1754969.013      439495.318     1755278.583      439156.851
     1755409.787      439173.251     1755523.609      439258.618
      1755922.22      439258.618
#Sta/Elev= 30
       0  1022.6    99.7  1016.4   159.5 1010.48   249.3 1008.32   299.1 1008.18
   368.9 1004.79   408.8  992.12   418.8  992.76   438.7  997.45   458.7  998.61
   468.1  995.31   505.9   971.1     510 969.941   515.4  968.41   524.8   967.9
   534.2  970.03   544.4  975.01   553.1  977.49   743.2  978.51     793  980.82
   852.8  986.05   862.7  993.28   872.7 1003.36   882.7 1010.87   892.6 1016.96
   922.5 1032.31   972.4 1052.79    1062  1080.3  1091.9 1087.03  1131.8  1093.1
#Mann= 3 , 0 , 0
       0     .06       0     510    .045       0   544.4     .06       0
Bank Sta=510,544.4
XS Rating Curve= 0 ,0
Exp/Cntr=0.3,0.1

Type RM Length L Ch R = 1 ,9892.1  ,418.3,426.5,434.6
XS GIS Cut Line= 5
     1755132.247      439417.232     1755133.757      439415.164
     1755135.922       439414.88      1755218.42      439404.077
     1755854.853      439320.736
#Sta/Elev= 30
       0 1012.16    97.8 1008.18   107.7 1006.57   117.6  999.66   127.4  995.14
   147.2  998.09     167  995.88   186.7 1004.54   196.6 1004.44   216.3   997.6
   226.2  992.86   236.1  985.24   265.7  971.29   275.6   968.5   285.4   967.9
   295.3   967.9   315.1  976.01   394.1  976.38   463.2  978.26   542.2  983.95
   552.1  992.03   561.9    1005   581.7 1020.63   591.6 1026.64   601.4 1031.92
   621.2 1040.37   650.8 1056.81   660.7 1058.74   700.2 1080.17   729.8 1091.29
#Mann= 3 , 0 , 0
       0     .06       0   265.7    .045       0   315.1     .06       0
Bank Sta=265.7,315.1
XS Rating Curve= 0 ,0
Exp/Cntr=0.3,0.1

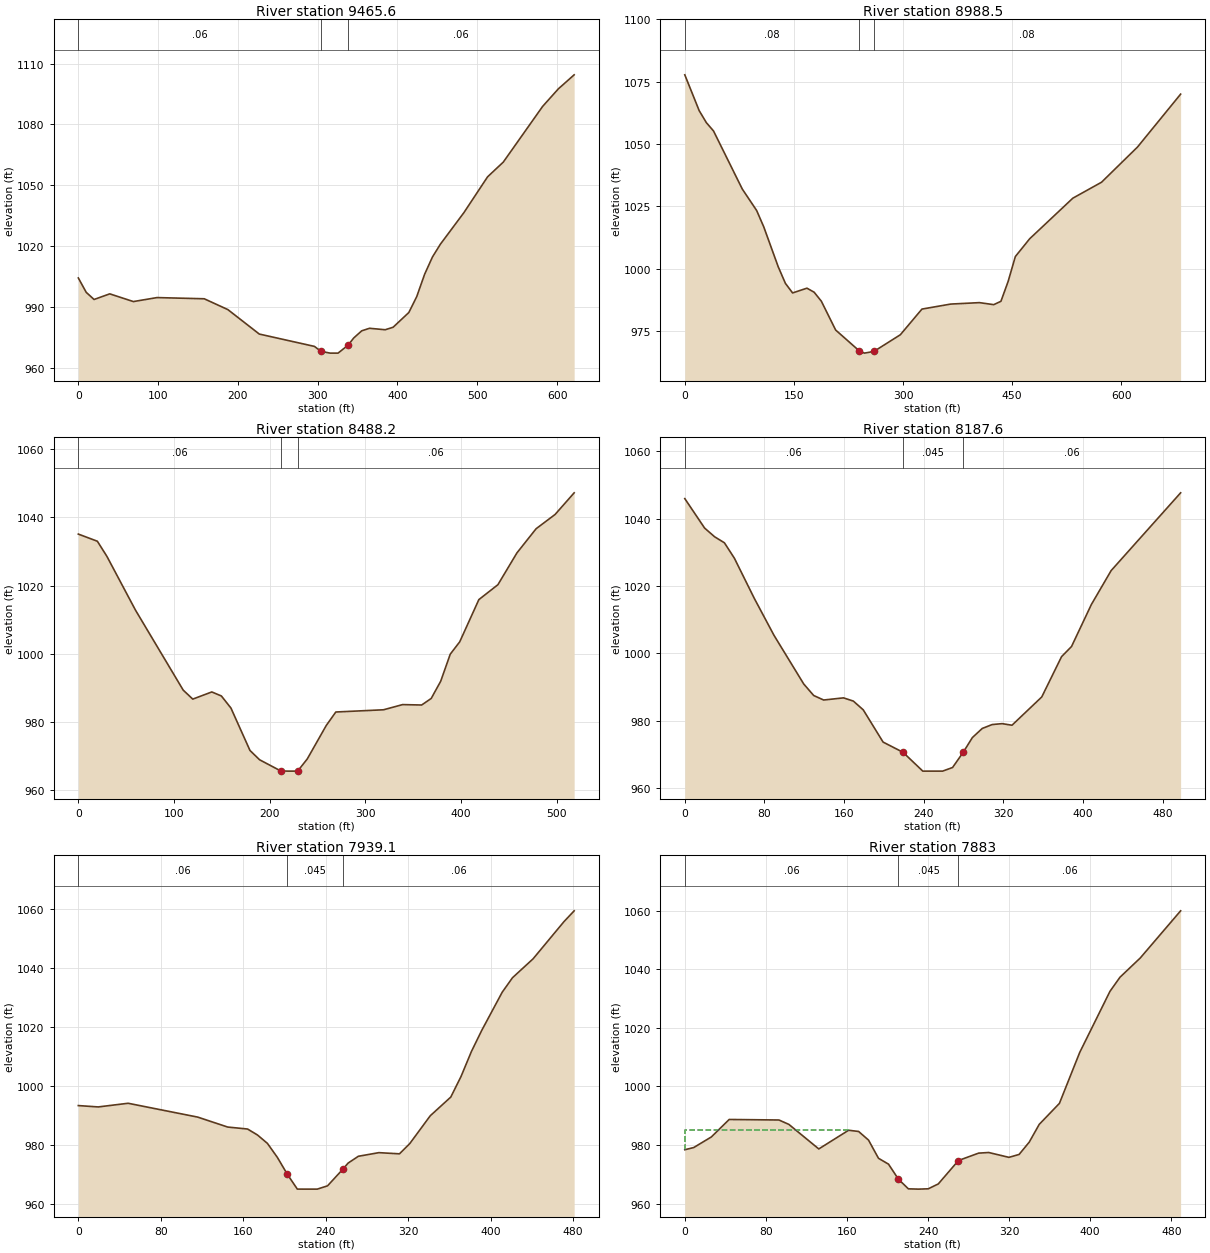
Type RM Length L Ch R = 1 ,9465.6  ,482.6,477.1,471.6
XS GIS Cut Line= 2
     1755239.374      439690.118     1755842.127      439841.029
#Sta/Elev= 30
       0 1004.24     9.9  997.14    19.7  993.62    39.4   996.4      69  992.59
    98.6  994.56   157.8  993.97   187.4  988.63   226.8  976.56   295.9  970.47
   304.2968.0135   315.6  967.15   325.5  967.15   337.8970.9849   345.2  974.64
   355.1  978.14   364.9  979.41   384.6  978.69   394.5  979.92   414.2  987.19
   424.1  995.03     434 1006.07   443.8 1014.58   453.7 1020.87   483.3 1036.52
   512.9 1054.15   532.6 1061.42   581.9  1088.9   601.6 1097.56   621.4 1104.48
#Mann= 3 , 0 , 0
       0     .06       0   304.2    .045       0   337.8     .06       0
Bank Sta=304.2,337.8
XS Rating Curve= 0 ,0
Exp/Cntr=0.3,0.1

Type RM Length L Ch R = 1 ,8988.5  ,510.2,500.3,490.5
XS GIS Cut Line= 2
     1755166.327      440224.942     1755847.893      440225.563
#Sta/Elev= 30
       0 1077.79    19.8 1063.41    29.6 1058.62    39.5 1055.26      79 1031.98
    98.8 1023.35   108.7 1016.68   128.4  1000.8   138.3  994.12   148.2  990.28
   167.9  992.19   177.8  990.57   187.7  986.97   207.4  975.39     240966.9965
   246.9  966.13   259.9966.7938   296.3   973.5     326   983.8   365.5  985.81
     405  986.39   424.7  985.58   434.6  986.93   444.5  994.91   454.4 1004.88
   474.1 1012.01   533.4 1028.29   572.9  1034.7   622.3 1048.81   681.6 1070.04
#Mann= 3 , 0 , 0
       0     .08       0     240    .045       0   259.9     .08       0
Bank Sta=240,259.9
XS Rating Curve= 0 ,0
Exp/Cntr=0.3,0.1

Type RM Length L Ch R = 1 ,8488.2  ,300.8,300.6,300.4
XS GIS Cut Line= 2
     1755435.256        440762.8     1755906.319      440546.738
#Sta/Elev= 30
       0 1035.12    19.9 1033.02    29.9 1028.57    59.8 1012.78   109.6  989.36
   119.6  986.72   139.5  988.82   149.5  987.64   159.5   984.1   179.4  971.66
   189.4  968.94   211.5965.6608   219.3   965.6   229.2   965.6   239.2  969.14
   259.1  978.98   269.1  982.94   318.9  983.59   338.9  985.11   358.8  984.99
   368.8  986.91   378.7  991.95   388.7   999.9   398.6 1003.52   418.6  1015.9
   438.5 1020.27   458.4  1029.6   478.4 1036.68   498.3 1040.88   518.2 1047.22
#Mann= 3 , 0 , 0
       0     .06       0   211.5    .045       0   229.2     .06       0
Bank Sta=211.5,229.2
XS Rating Curve= 0 ,0
Exp/Cntr=0.3,0.1

Type RM Length L Ch R = 1 ,8187.6  ,251,248.4,248.1
XS GIS Cut Line= 2
     1755577.431      441025.768     1756027.863        440813.2
#Sta/Elev= 30
       0 1045.97    19.9 1037.22    29.9 1034.64    39.8 1032.84    49.8 1028.27
    69.7 1016.39    89.6 1005.35   119.5  990.88   129.5  987.46   139.5  986.12
   159.4  986.76   169.3  985.81   179.3  983.19   199.2  973.62   219.2  970.59
   239.1  964.99     259  964.99     269  966.07   279.7  970.59   288.9  974.96
   298.8  977.67   308.8  978.83   318.8   979.1   328.7  978.63   358.6  987.03
   378.5  999.01   388.5 1002.02   408.4 1014.48   428.3 1024.58   498.1 1047.69
#Mann= 3 , 0 , 0
       0     .06       0   219.2    .045       0   279.7     .06       0
Bank Sta=219.2,279.7
XS Rating Curve= 0 ,0
Exp/Cntr=0.3,0.1

Type RM Length L Ch R = 1 ,7939.1  ,56.3,56.2,54.8
XS GIS Cut Line= 3
     1755707.645      441266.163     1755904.972      441144.523
     1756131.337      441040.047
#Sta/Elev= 30
       0  993.28    19.3  992.82    48.3  994.06   115.9  989.37   144.9  986.01
   164.2  985.34   173.8  983.33   183.5  980.47   193.2   975.7   202.8  970.01
   212.5     965   220.2  964.99   231.8  964.99   241.8   966.1     257971.8625
   261.7  973.79   271.7  976.11   291.6  977.34   311.6  976.94   321.6  980.41
   341.5  989.84   361.4  996.16   371.4 1003.18   381.4 1011.58   391.4 1018.72
   411.3 1031.67   421.3 1036.58   441.2 1042.95   471.2 1055.55   481.1 1059.22
#Mann= 3 , 0 , 0
       0     .06       0   202.8    .045       0     257     .06       0
Bank Sta=202.8,257
XS Rating Curve= 0 ,0
Exp/Cntr=0.3,0.1

Type RM Length L Ch R = 1 ,7883    ,380.4,386.7,387.8
XS GIS Cut Line= 4
     1755747.617      441339.957     1755761.302      441298.395
     1755936.925      441190.133     1756154.081      441089.908
#Sta/Elev= 30
       0  978.43     8.8  979.17    26.2  982.79    43.8  988.75    92.9  988.57
   102.7  987.07   132.2   978.7   161.6  985.07   171.5  984.66   181.3   981.7
   191.1  975.51     201  973.51   210.8  968.36   220.6  965.09   230.4  964.99
   240.2   965.1   250.1  966.76     270  974.75   289.9  977.27   299.9  977.48
   319.8  975.83   329.8  976.81   339.8     981   349.7  987.08   369.6  994.23
   389.6 1011.58   419.5 1032.46   429.4 1037.28   449.4 1043.84   489.2 1059.92
#Mann= 3 , 0 , 0
       0     .06       0   210.8    .045       0     270     .06       0
#XS Ineff= 2 , 0
          163.42     985
Permanent Ineff=
       F       F
Bank Sta=210.8,270
XS Rating Curve= 0 ,0
Exp/Cntr=0.3,0.1

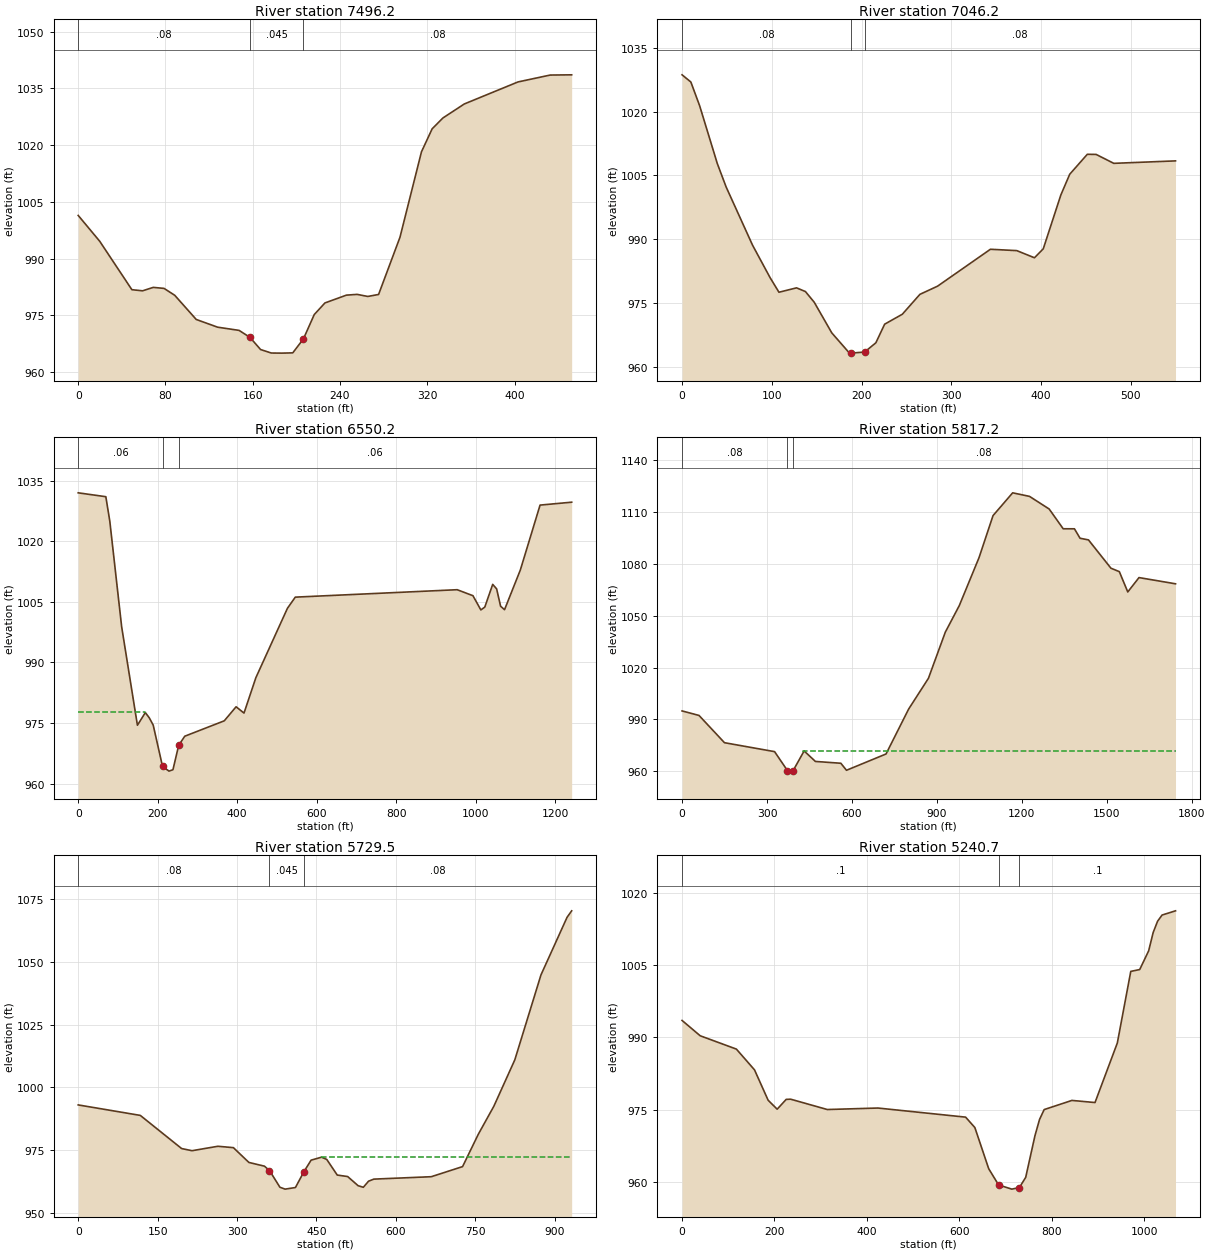
Type RM Length L Ch R = 1 ,7496.2  ,448.4,450,451.4
XS GIS Cut Line= 2
     1755899.775      441620.864     1756320.886      441455.596
#Sta/Elev= 30
       0 1001.39    19.7  994.57    49.2  981.76      59  981.46    68.8  982.37
    78.7   982.1    88.5  980.28   108.2  973.89   127.8  971.85   147.5     971
   157.4  969.17   167.2  965.94     177  965.02   186.8  964.99   196.7  965.06
   206.5  968.76   216.4  975.18   226.2  978.26   245.9  980.32   255.7  980.52
   265.5  979.97   275.4   980.5     295  995.62   314.7  1018.2   324.5 1024.29
   334.4 1027.16     354 1030.86   403.2 1036.68   432.7  1038.5   452.4 1038.56
#Mann= 3 , 0 , 0
       0     .08       0   157.4    .045       0   206.5     .08       0
Bank Sta=157.4,206.5
XS Rating Curve= 0 ,0
Exp/Cntr=0.3,0.1

Type RM Length L Ch R = 1 ,7046.2  ,518.1,496,473.9
XS GIS Cut Line= 3
     1755962.993      442049.598     1756450.258      441896.948
     1756462.951      441859.668
#Sta/Elev= 30
       0 1028.65     9.8 1026.96    19.6 1021.37    39.3 1007.76    49.1 1002.27
    78.6  988.55    98.2  980.89     108  977.49   127.6  978.52   137.5  977.65
   147.3  975.14   166.9  967.92   186.6  963.16   188.5  963.16   203.5  963.42
     216  965.59   225.8  969.97   245.5  972.31   265.1  976.99   284.8  978.92
   343.7   987.6   373.1  987.28   392.8   985.6   402.6  987.71   422.2 1000.38
   432.1 1005.26   451.7 1009.95   461.5 1009.92   481.2 1007.82     550  1008.4
#Mann= 3 , 0 , 0
       0     .08       0   188.5    .045       0   203.5     .08       0
Bank Sta=188.5,203.5
XS Rating Curve= 0 ,0
Exp/Cntr=0.3,0.1

Type RM Length L Ch R = 1 ,6550.2  ,734.7,733,744.7
XS GIS Cut Line= 2
      1756463.45      442495.423     1756822.249      441306.731
#Sta/Elev= 30
       0 1032.01    69.5 1031.05    79.5 1024.99   109.3  998.84     149  974.44
   168.9  977.57   178.8  976.28   188.7  974.48   212.2964.2172   228.5  963.07
   238.4  963.42   252.9969.4852   268.2  971.72   367.5  975.53   397.3  979.01
   417.2  977.45     447   986.2   526.5 1003.41   546.3 1006.17   953.6 1008.01
   993.3 1006.53  1013.2    1003  1023.1  1003.7    1043 1009.33  1052.9 1008.22
  1062.9 1003.92  1072.8 1003.06  1112.5 1012.88  1162.2 1028.97  1241.7 1029.69
#Mann= 3 , 0 , 0
       0     .06       0   212.2    .045       0   252.9     .06       0
#XS Ineff= 2 , 0
          168.17  977.63
Permanent Ineff=
       F       F
Bank Sta=212.2,252.9
XS Rating Curve= 0 ,0
Exp/Cntr=0.3,0.1

Type RM Length L Ch R = 1 ,5817.2  ,88.6,87.7,82.7
XS GIS Cut Line= 5
     1756933.998      442470.534     1757232.734      442448.615
     1757249.535      442368.588     1757630.064      442015.988
     1757893.417      441215.326
#Sta/Elev= 30
       0  994.91    59.9  992.29   149.8  976.53   326.8  971.36   372.3 960.395
   381.3  960.09   391.3  960.09   431.2  971.76   471.1  965.69   560.9  964.64
   580.8  960.58   720.5  970.01   800.3  995.97   870.2 1013.75   929.8 1040.44
   979.4 1055.88  1048.8 1083.48  1098.4 1107.86  1167.8 1121.04  1227.3 1118.98
  1296.7 1111.68  1346.3 1100.25    1386 1100.23  1405.8 1094.77  1435.6 1093.81
  1514.9 1077.45  1544.6 1075.45  1574.4 1063.71    1614 1072.02    1743 1068.43
#Mann= 3 , 0 , 0
       0     .08       0   372.3    .045       0   391.3     .08       0
#XS Ineff= 2 , 0
                          428.88          971.71
Permanent Ineff=
       F       F
Bank Sta=372.3,391.3
XS Rating Curve= 0 ,0
Exp/Cntr=0.3,0.1

Type RM Length L Ch R = 1 ,5729.5  ,434.2,488.8,529
XS GIS Cut Line= 5
     1756990.422      442485.725     1757302.517      442505.585
     1757322.594      442409.955      1757699.01      442061.167
     1757701.876      442052.978
#Sta/Elev= 30
       0  992.94   117.3  988.76   195.4  975.54     215  974.68   263.9  976.45
   293.2   975.9   322.5     970   351.8  968.52   361.4 966.776   381.1  960.11
   390.9  959.36   410.4     960   426.6 966.365     440  970.91   459.8  972.11
   469.6   971.2   489.4  964.97   509.1  964.37   528.9  960.72   538.7   960.1
   548.6  962.53   558.5  963.35     667  964.31   726.2  968.34   755.8  981.19
   785.4  992.46   824.9 1010.92   874.3 1044.78   923.6 1067.74   932.3 1070.34
#Mann= 3 , 0 , 0
       0     .08       0   361.4    .045       0   426.6     .08       0
#XS Ineff= 2 , 0
                          458.81          972.32
Permanent Ineff=
       F       F
Bank Sta=361.4,426.6
XS Rating Curve= 0 ,0
Exp/Cntr=0.3,0.1

Type RM Length L Ch R = 1 ,5240.7  ,104.4,91.6,83.3
XS GIS Cut Line= 5
     1757029.877      442501.696     1757303.314      442525.134
     1757494.721      442631.904     1757838.471      442836.332
     1758012.082      442850.654
#Sta/Elev= 30
       0  993.51    39.2  990.33   117.6  987.56   156.8  983.25   186.2  976.96
   205.8  975.09   225.4  977.13   235.2  977.16   314.3  975.02   423.9  975.33
   613.6  973.44   633.6  971.28   663.6  962.73     685 959.367   713.6   958.5
     730 958.833   743.6  960.94   763.6  969.57   773.6  972.97   783.6  975.01
   843.6  976.91   893.6  976.47   941.9  988.83     971 1003.69   990.3 1004.07
  1009.7 1007.96  1019.4 1011.74    1029  1014.1  1038.7 1015.38  1067.8 1016.26
#Mann= 3 , 0 , 0
       0      .1       0     685    .045       0     730      .1       0
Bank Sta=685,730
XS Rating Curve= 0 ,0
Exp/Cntr=0.3,0.1

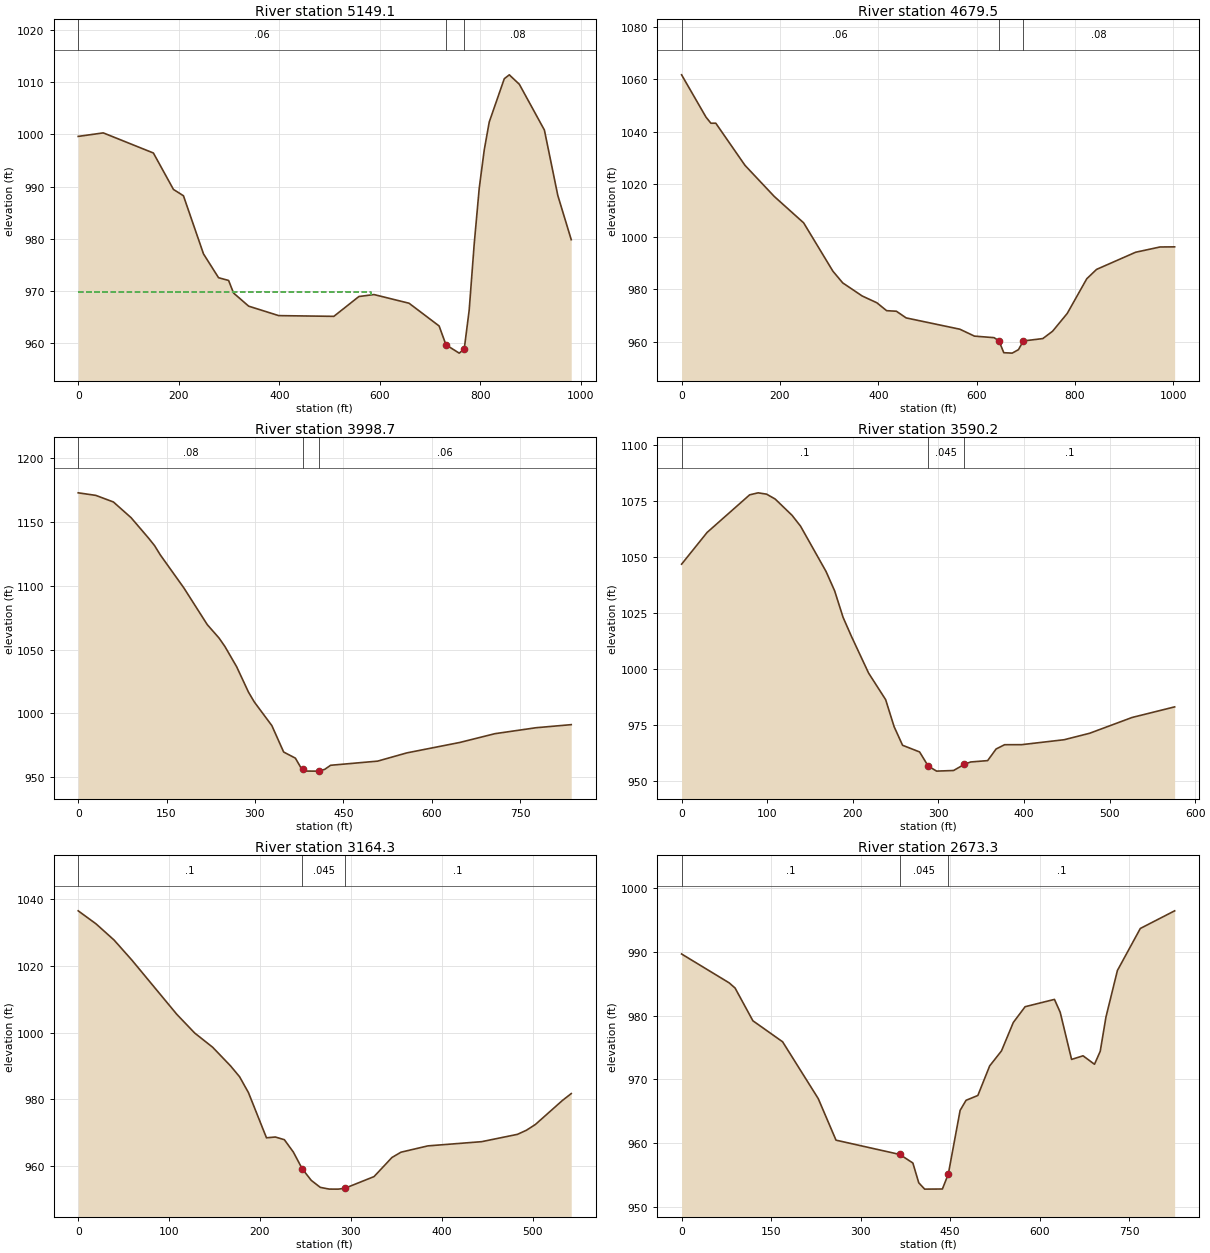
Type RM Length L Ch R = 1 ,5149.1  ,472.4,469.6,465.9
XS GIS Cut Line= 3
     1756985.048      442510.843     1757826.194      442901.468
     1757879.245      442907.289
#Sta/Elev= 30
       0  999.63    49.9 1000.31   149.6  996.44   189.5  989.44   209.4  988.22
   249.3  977.04   279.2  972.47   299.2  971.94   309.1  969.52   339.1     967
   398.9  965.18   508.6  965.04   558.4  968.85   588.4  969.23   658.2  967.56
     718  963.19   731.6 959.566   757.9  957.97   767.9  958.73   777.8  966.23
   787.8  978.97   797.8  989.69   807.8  997.06   817.7  1002.4   847.6 1010.72
   857.6 1011.47   877.6 1009.65   927.4 1000.86   954.1  988.28   980.8  979.78
#Mann= 3 , 0 , 0
       0     .06       0   731.6    .045       0   767.9     .08       0
#XS Ineff= 2 , 0
          582.82  969.64
Permanent Ineff=
       F       F
Bank Sta=731.6,767.9
XS Rating Curve= 0 ,0
Exp/Cntr=0.3,0.1

Type RM Length L Ch R = 1 ,4679.5  ,708.9,680.8,653.5
XS GIS Cut Line= 2
     1756740.937      442993.769     1757698.774      443290.007
#Sta/Elev= 30
       0 1061.74    49.6 1045.62    59.6 1043.28    69.5  1043.3     129 1027.21
   188.6 1015.34   248.2  1005.3   307.7  986.87   327.6  982.42   367.3  977.41
   397.1  974.83   416.9  971.82   436.8   971.6   456.6  969.06   565.8  964.75
   595.6  962.11   635.3  961.53   645.2  960.38   655.2  955.79   672.3  955.63
     685  956.95   694.9  960.27   734.6  961.18   754.4  963.98   784.2  970.76
   823.9  983.98   843.8  987.55   923.2  994.09   972.8   996.1  1002.6  996.15
#Mann= 3 , 0 , 0
       0     .06       0   645.2    .045       0   694.9     .08       0
Bank Sta=645.2,694.9
XS Rating Curve= 0 ,0
Exp/Cntr=0.3,0.1

Type RM Length L Ch R = 1 ,3998.7  ,425.5,408.5,391.5
XS GIS Cut Line= 2
     1757186.783      444086.793     1757687.534      443416.062
#Sta/Elev= 30
       0 1172.99    29.9 1170.99    59.8 1165.81    89.7 1153.54   119.6  1137.4
   129.5 1131.68   139.5 1124.23   179.4 1098.41   219.2 1069.58   239.2 1059.05
   249.1 1052.46     269 1036.59     289 1016.77   298.9 1009.01   328.8  990.41
   348.8  969.71   368.7  964.91   378.7  956.95     382956.2267   388.6  954.78
   398.6  954.73   408.6  954.73   418.5  956.12   428.5  959.31   508.2  962.56
     558  969.04   647.7   977.2   707.5   984.1   777.2  988.76     837  991.18
#Mann= 3 , 0 , 0
       0     .08       0     382    .045       0   408.6     .06       0
Bank Sta=382,408.6
XS Rating Curve= 0 ,0
Exp/Cntr=0.3,0.1

Type RM Length L Ch R = 1 ,3590.2  ,439.9,425.8,412.2
XS GIS Cut Line= 2
     1757852.993      444159.162     1757787.948      443586.764
#Sta/Elev= 30
       0 1046.75    29.8 1060.87    79.5 1077.61    89.4 1078.51    99.3 1077.92
   109.3 1075.76   129.1 1068.49     139 1063.66   168.8 1043.48   178.8  1034.9
   188.7 1023.06   198.6 1014.48   218.5  998.26   238.4  986.45   248.3  974.42
   258.2  966.11   278.1  963.14   288.2956.8148     298   954.6   317.8  954.88
   330.5957.6445   337.7  958.67   357.6  959.28   367.5  964.46   377.4  966.36
   397.3  966.38     447  968.58   476.8  971.46   526.4  978.49   576.1   983.2
#Mann= 3 , 0 , 0
       0      .1       0   288.2    .045       0   330.5      .1       0
Bank Sta=288.2,330.5
XS Rating Curve= 0 ,0
Exp/Cntr=0.3,0.1

Type RM Length L Ch R = 1 ,3164.3  ,498.7,491,482.7
XS GIS Cut Line= 2
     1758384.481      443879.236     1758019.481      443477.736
#Sta/Elev= 30
       0 1036.41    19.7  1032.5    39.5 1027.67    59.2 1021.64   108.5 1005.47
   128.2  999.87     148  995.61   167.7  990.03   177.6   986.8   187.4  982.04
   207.2  968.54     217  968.77   226.9  967.97   236.8  964.27   246.6  959.24
   256.5  955.81   266.4  953.72   276.2   953.2   286.1  953.19   293.5953.4456
   325.6  956.94   345.3  962.65   355.2  964.23   384.8  966.12     444  967.38
   483.4  969.57   493.3   970.8   503.2  972.53   532.8  979.68   542.6  981.76
#Mann= 3 , 0 , 0
       0      .1       0   246.6    .045       0   293.5      .1       0
Bank Sta=246.6,293.5
XS Rating Curve= 0 ,0
Exp/Cntr=0.3,0.1

Type RM Length L Ch R = 1 ,2673.3  ,91.6,91.7,91.7
XS GIS Cut Line= 4
     1758618.158      443644.628     1758663.257      443399.805
     1758340.848      443225.874      1758368.09      443016.604
#Sta/Elev= 30
       0  989.68    79.7  985.15    89.6  984.34   119.5  979.19   169.3  975.89
     229  966.97   258.8  960.44   365.8 958.192   387.6  956.85   397.5  953.74
   407.4  952.75   437.1  952.77     447  955.12   466.8  965.12   476.7   966.7
   496.5  967.46   516.3   972.1   536.1  974.46   555.9  978.92   575.7   981.4
   624.9  982.55   634.5  980.53   653.6  973.12   672.8  973.69     692  972.36
   701.6   974.4   711.2  979.78   730.4  987.09   768.8  993.69   826.3  996.46
#Mann= 3 , 0 , 0
       0      .1       0   365.8    .045       0     447      .1       0
Bank Sta=365.8,447
XS Rating Curve= 0 ,0
Exp/Cntr=0.3,0.1

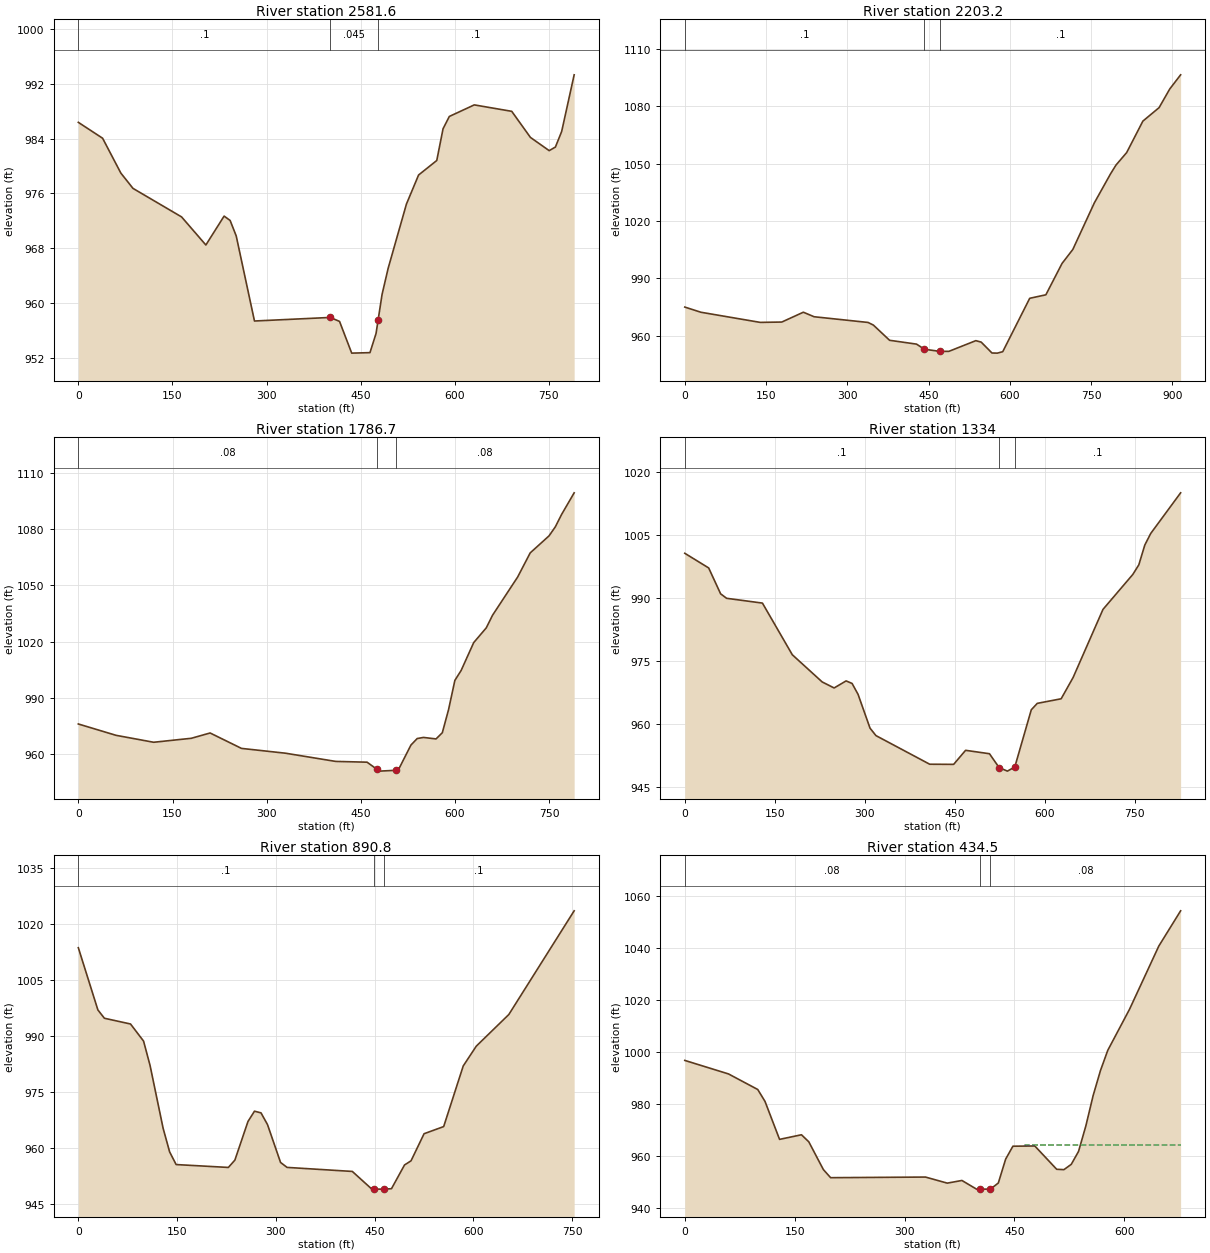
Type RM Length L Ch R = 1 ,2581.6  ,348.4,378.4,408.5
XS GIS Cut Line= 4
     1758652.962      443608.242     1758709.921      443323.445
     1758463.872      443187.694     1758490.288      442970.367
#Sta/Elev= 30
       0  986.37    38.7  984.05    67.8  978.96    87.1  976.73   164.6  972.56
   203.3  968.46   232.4  972.68     242  972.04   251.7  969.78   280.8  957.36
   401.6  957.88   416.4   957.3   435.8  952.67   464.9  952.74   474.6  955.54
   477.9957.5028   484.2  961.25   493.9  965.06     523  974.43   542.4  978.68
   571.4   980.8   581.4  985.43   591.4  987.23   631.2  988.92   690.9  987.98
   720.7  984.17   750.6  982.24   760.5  982.76   770.5  985.04   790.4  993.31
#Mann= 3 , 0 , 0
       0      .1       0   401.6    .045       0   477.9      .1       0
Bank Sta=401.6,477.9
XS Rating Curve= 0 ,0
Exp/Cntr=0.3,0.1

Type RM Length L Ch R = 1 ,2203.2  ,408.4,416.5,424.4
XS GIS Cut Line= 2
     1758796.005      443681.545     1759024.402      442795.149
#Sta/Elev= 30
       0  975.06    29.8  972.35   139.3  967.05   179.1  967.23   218.9  972.37
   238.8     970   338.3  967.02   348.2  965.64   378.1  957.69   427.8  955.69
   442.5952.9969     471   951.9   487.5   951.9   537.3   957.5   547.2  956.74
   567.1  951.05   577.1  950.98     587  951.73   636.8  979.65   666.6  981.47
   696.5  997.88   716.4 1005.19   756.2 1029.59     786 1044.71     796 1049.28
   815.8 1055.84   845.7 1072.28   875.6 1079.32   895.4 1089.12   915.4 1096.49
#Mann= 3 , 0 , 0
       0      .1       0   442.5    .045       0     471      .1       0
Bank Sta=442.5,471
XS Rating Curve= 0 ,0
Exp/Cntr=0.3,0.1

Type RM Length L Ch R = 1 ,1786.7  ,444.4,452.7,461
XS GIS Cut Line= 2
     1759008.683      443806.451     1759458.254      443157.119
#Sta/Elev= 30
       0   976.1      60  970.06     120  966.35     180  968.47   209.9   971.3
   259.9  963.08   329.9  960.52   409.9  956.14   459.9  955.73   475.3952.0318
   479.9  950.96   505.6  951.39   509.9  951.72   529.8  964.86   539.8  968.34
   549.8  968.93   569.8  968.13   579.8  971.44   589.8  983.85   599.8  999.36
   609.8 1004.66   629.8  1019.5   649.8 1027.36   659.8 1034.09   699.8 1054.47
   719.8 1067.34   749.8 1076.42   759.8 1081.23   769.8 1087.84   789.8 1099.37
#Mann= 3 , 0 , 0
       0     .08       0   475.3    .045       0   505.6     .08       0
Bank Sta=475.3,505.6
XS Rating Curve= 0 ,0
Exp/Cntr=0.3,0.1

Type RM Length L Ch R = 1 ,1334    ,438.9,443.1,447.1
XS GIS Cut Line= 2
     1759164.305      444016.754     1759847.979       443552.46
#Sta/Elev= 30
       0 1000.68    39.8  997.19    59.7  991.04    69.7  989.97   129.4  988.83
   179.2  976.54     229  970.07   248.9  968.64   268.8  970.32   278.8  969.72
   288.8  967.12   308.7  959.09   318.6  957.31   408.2   950.5   448.1  950.47
     468  953.81   507.8     953   523.9949.6992   537.7  948.86     550  949.84
   577.5  963.45   587.5  964.98   627.3  966.07   647.2  971.13     697  987.33
   746.8  995.66   756.7  997.92   766.7 1002.64   776.6  1005.4   826.4 1015.06
#Mann= 3 , 0 , 0
       0      .1       0   523.9    .045       0     550      .1       0
Bank Sta=523.9,550
XS Rating Curve= 0 ,0
Exp/Cntr=0.3,0.1

Type RM Length L Ch R = 1 ,890.8   ,456.5,456.4,456.4
XS GIS Cut Line= 2
     1759362.779      444303.231     1760051.971      443999.506
#Sta/Elev= 30
       0 1013.54    29.7  996.87    39.6  994.64    79.3   993.1    99.1  988.52
     109  981.96   128.8  965.16   138.7  958.83   148.6  955.44   227.9  954.67
   237.8  956.63   257.7  966.98   267.6  969.74   277.5  969.29   287.4  966.14
   307.2  956.01   317.1  954.68   416.2   953.6   445.9  948.86     449  948.86
     464  948.86   475.7  948.97   495.5  955.33   505.4  956.44   525.2   963.7
     555  965.62   584.7  981.86   604.5  987.16     654  995.65   753.2 1023.42
#Mann= 3 , 0 , 0
       0      .1       0     449    .045       0     464      .1       0
#XS Ineff= 2 , 0
          269.97  969.62
Permanent Ineff=
       F       F
Bank Sta=449,464
XS Rating Curve= 0 ,0
Exp/Cntr=0.3,0.1

Type RM Length L Ch R = 1 ,434.5   ,371.9,375.2,378.3
XS GIS Cut Line= 2
     1759607.876      444657.004     1760227.838      444384.916
#Sta/Elev= 30
       0  996.82    59.7  991.63    99.6  985.66   109.5   981.1   129.4  966.52
   159.3  968.29   169.3  965.59   189.2  954.94   199.1  951.82   328.6  952.06
   358.4  949.73   378.4  950.75   398.3  947.43   402.4  947.43   417.4  947.43
   428.1  949.79   438.1  958.95     448   963.9   477.9  963.99   507.8  955.04
   517.7  954.91   527.7  956.95   537.6  961.89   547.6  971.69   557.6  983.39
   567.5  992.88   577.5 1000.67   607.3 1016.48   647.2 1040.69     677 1054.22
#Mann= 3 , 0 , 0
       0     .08       0   402.4    .045       0   417.4     .08       0
#XS Ineff= 2 , 0
                          465.01          964.34
Permanent Ineff=
       F       F
Bank Sta=402.4,417.4
XS Rating Curve= 0 ,0
Exp/Cntr=0.3,0.1

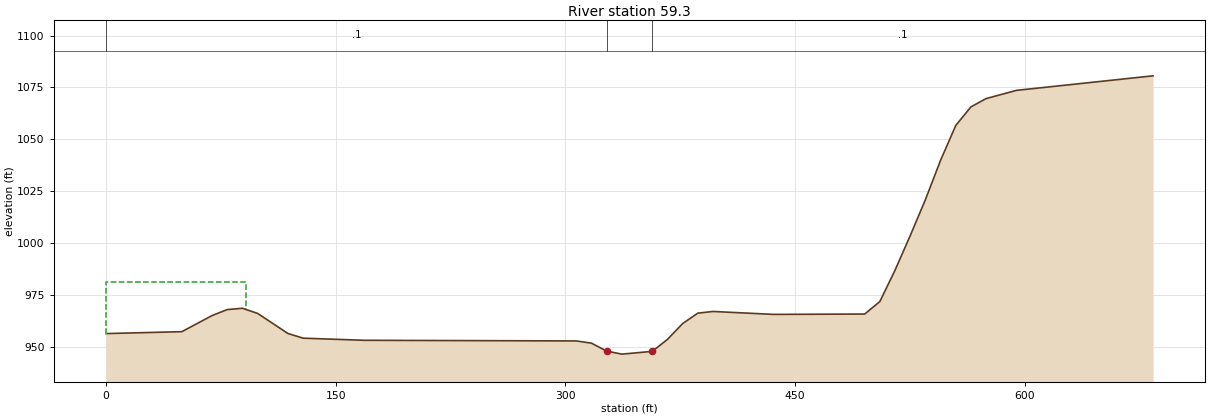
Type RM Length L Ch R = 1 ,59.3    ,54.6,59.3,64
XS GIS Cut Line= 2
     1759759.046      444941.118     1760417.567      444756.933
#Sta/Elev= 30
       0  956.38    49.6   957.3    69.4   965.1    79.3  967.95    89.2  968.58
    99.1  966.09   118.9  956.42   128.8  954.17   168.5  953.15   307.2  952.83
   317.1  951.76     327  947.95   336.9  946.48   356.8  947.81   366.7  953.58
   376.6  961.19   386.5  966.22   396.4  967.04     436  965.63   495.5   965.8
   505.4  971.82   515.3  986.91   525.2 1003.53   535.1 1020.84     545  1039.8
     555 1056.71   564.9 1065.65   574.8 1069.64   594.6  1073.6   683.8 1080.61
#Mann= 3 , 0 , 0
       0      .1       0     327    .045       0   356.8      .1       0
#XS Ineff= 2 , 0
           91.27  981.29
Permanent Ineff=
       F       F
Bank Sta=327,356.8
XS Rating Curve= 0 ,0
Exp/Cntr=0.3,0.1

Chan Stop Cuts=-1
Use User Specified Reach Order=0
Composite Channel Slope=5